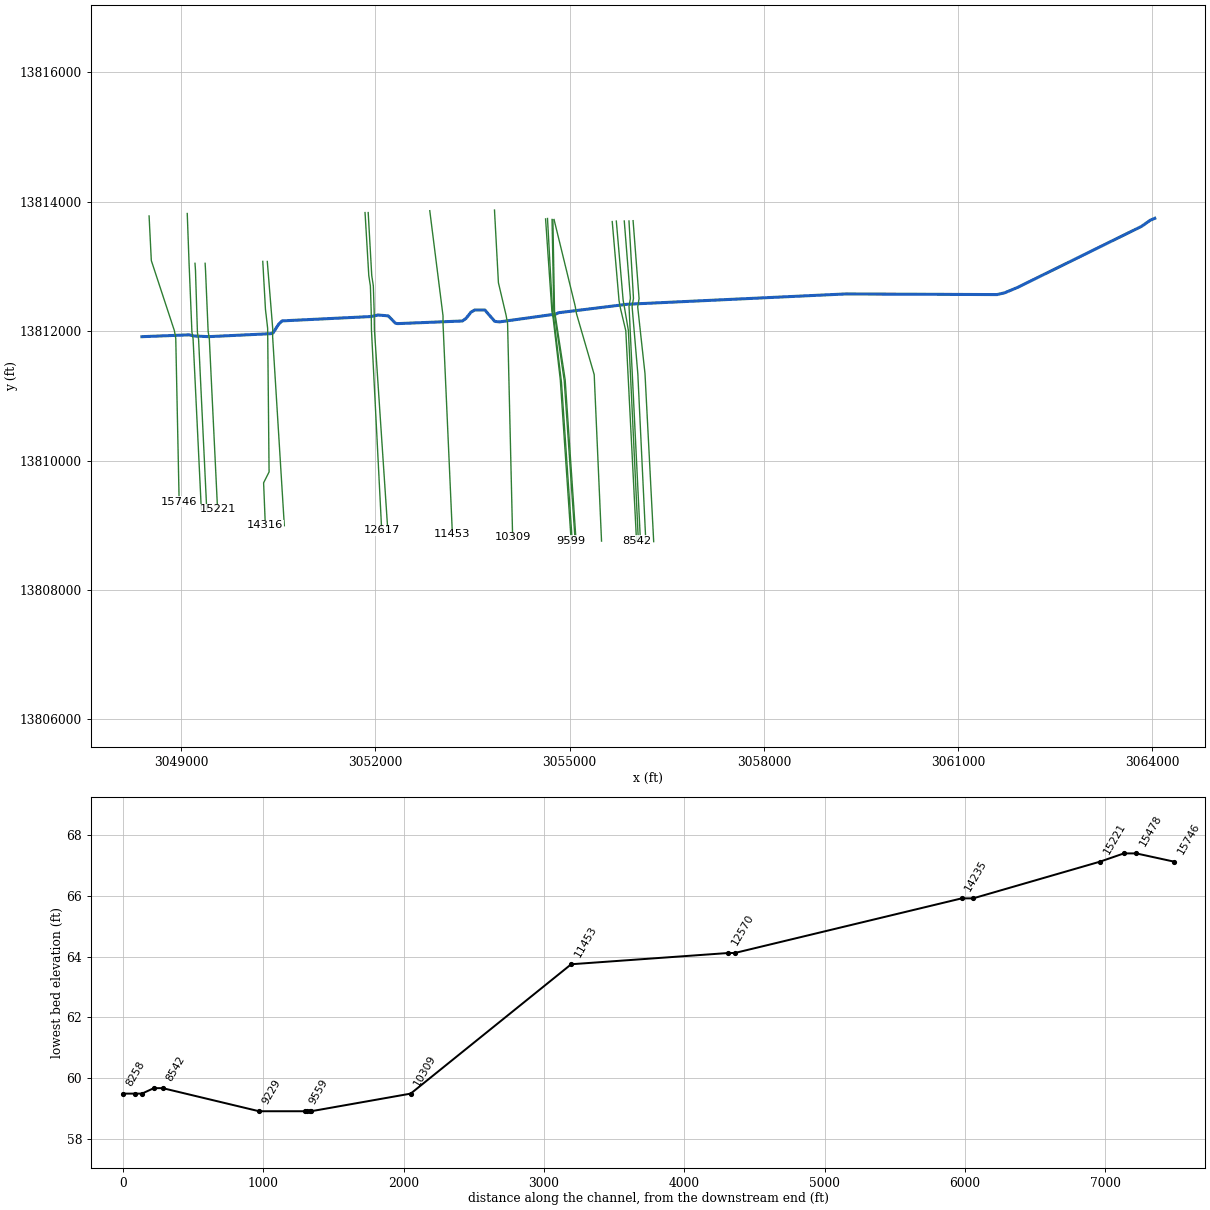
--- D120-00-00.prj (project) ---

Proj Title=D120-00-00
Current Plan=p02
Default Exp/Contr=.3,.1
English Units
Geom File=g01
Flow File=f01
Flow File=f02
Flow File=f07
Plan File=p02
Plan File=p03
Plan File=p05
Y Axis Title=Elevation
X Axis Title(PF)=Main Channel Distance
X Axis Title(XS)=Station
BEGIN DESCRIPTION:
Brays Bayou Watershed
Tributary 20.90
HCFCD Unit D120-00-00
Flood Hazard & Floodway Model
10, 2, 1, 0.2% Event
Filename D120.prj
Prepared by: Dodson & Associates, Inc.   Date: September 2003
Reviewed by:____________________	 Date:_________
STATUS (Final RAS, SVSQ)
FOR FLOOD HARZARD RECOVERY DATA ONLY,03/02/2004
Will Be Voided Upon Release of The Preliminary DFIRM
END DESCRIPTION:
DSS Export Rating Curves= 0
DSS Export Rating Curve Sorted= 0
DSS Export Volume Flow Curves= 0
DXF OffsetX= 0
DXF OffsetY= 0
DXF ScaleX= 1
DXF ScaleY= 10

--- D120-00-00.p02 (plan) ---

Plan Title=FEMA Effective June 2007
Version=Version 3.0.1  Mar 2001
Short Identifier=FEMAeff0607
Geom File=g01
Flow File=f01
Subcritical Flow
K Sum by GR= 0
Std Step Tol= 0.01
Critical Tol= 0.01
Num of Std Step Trials= 20
Max Error Tol= 0.3
Flow Tol Ratio= 0.001
Split Flow NTrial= 30
Split Flow Tol= 0.02
Split Flow Ratio= 0.02
Log Output Level= 0
Friction Slope Method= 1
Unsteady Friction Slope Method= 2
Parabolic Critical Depth
Global Vel Dist= 0 , 0 , 0
Global Log Level= 0
CheckData=True
Encroach Param=-1 ,0,0, 0
Computation Interval=1HOUR
Output Interval=1HOUR
Run HTab= 0
Run UNet= 0
Run PostProcess= 0
UNET Theta= 1
UNET ZTol= 0.02
UNET ZSATol= 0.1
UNET MxIter= 20
UNET MaxInSteps= 20
UNET DtIC= 0
UNET DtMin= 0
UNET MaxCRTS= 20
UNET WFStab= 2
UNET SFStab= 1
UNET WFX= 1
UNET SFX= 1
UNET Convert EG Bridges=-1
UNET Use Existing IB Tables=-1
Instantaneous Interval=1HOUR
Write IC File= 0
Write Velocity= 0
Write Detailed= 0

--- D120-00-00.p03 (plan) ---

Plan Title=Floodway
Version=Version 3.0.1  Mar 2001
Short Identifier=Floodway0607
Geom File=g01
Flow File=f02
Subcritical Flow
K Sum by GR= 0
Std Step Tol= 0.01
Critical Tol= 0.01
Num of Std Step Trials= 20
Max Error Tol= 0.3
Flow Tol Ratio= 0.001
Split Flow NTrial= 30
Split Flow Tol= 0.02
Split Flow Ratio= 0.02
Log Output Level= 0
Friction Slope Method= 1
Unsteady Friction Slope Method= 2
Parabolic Critical Depth
Global Vel Dist= 0 , 0 , 0
Global Log Level= 0
CheckData=True
Encroach Param=-1 ,0,0, 2
Encroach River=D120-00-00
Encroach Reach=Reach 0
Encroach Node=15746
       1 1858.13 1933.32
Encroach Node=15478
       1 1855.39 1897.59
Encroach Node=15434
       1 1091.39 1897.59
Encroach Node=15390
       1 1091.39 1133.59
Encroach Node=15221
       1 1084.13 1159.32
Encroach Node=14316
       1 1046.21 1166.23
Encroach Node=14235
       1 1061.36 1144.81
Encroach Node=13426
       1 1061.36 1624.21
Encroach Node=12617
       1 1532.88 1624.21
Encroach Node=12570
       1 1530.83 1622.52
Encroach Node=11453
       1 1659.74 1760.95
Encroach Node=10309
       1 1662.75 1746.77
Encroach Node=9599
       1 1418.72 1501.04
Encroach Node=9589
       1 1422.72 1505.04
Encroach Node=9579
       1 1402.72 1505.04
Encroach Node=9569
       1 1402.72 1485.04
Encroach Node=9559
       1 1393.72 1476.04
Encroach Node=9229
       1 1398.72 1481.04
Encroach Node=8542
       1 1241.31 1325.86
Encroach Node=8479
       1 1234.31 1318.86
Encroach Node=8394
       1 1231.18 1318.37
Encroach Node=8370
       1 1224.18 1318.37
Encroach Node=8346
       1 1224.18 1311.37
Encroach Node=8258
       1 1224.18 1311.37
Encroach Node=7826
       1 1184.37  1301.2
Encroach Node=7296
       1 1555.82 1686.52
Encroach Node=6869
       1 1609.15 1720.89
Encroach Node=6778
       1 1634.15 1745.89
Encroach Node=6729
       1 1634.15 1765.89
Encroach Node=6680
       1 1654.15 1765.89
Encroach Node=6601
       1 1658.53 1737.69
Encroach Node=6469
       1 1646.54 1737.09
Encroach Node=5677
       1 1690.22 1783.09
Encroach Node=4665
       1  1623.3 1710.44
Encroach Node=4603
       1  1626.3 1713.44
Encroach Node=4577
       1  1621.3 1713.44
Encroach Node=4551
       1  1621.3 1708.44
Encroach Node=4480
       1  1605.3 1692.44
Encroach Node=4416
       1 1152.81 1239.94
Encroach Node=3976
       1 1166.62 1254.58
Encroach Node=3447
       1 1171.81 1262.72
Encroach Node=3348
       1 1159.04 1294.06
Encroach Node=3199
       1 1153.38 1318.47
Encroach Node=3049
       1 1153.38 1318.47
Encroach Node=2860
       1  1192.9 1279.42
Encroach Node=2302
       1  1076.4 1164.38
Encroach Node=1567
       1   381.8  497.05
Encroach Node=1025
       1   513.2  648.17
Encroach Node=956
       1  537.79  646.75
Encroach Node=907
       1  537.79  669.75
Encroach Node=858
       1  560.79  669.75
Encroach Node=791
       1  561.79  670.75
Encroach Node=526
       1  615.68  714.21
Encroach Node=106
       1  767.57  869.04
Encroach Node=95
       1  783.04  856.83
Encroach Node=75
       1  769.29  834.75
Encroach Node=46
       1  761.18  893.34
Encroach Reach=D120-00-00_0001
Encroach Node=15746
       1 1858.13 1933.32
Encroach Node=15478
       1 1855.39 1897.59
Encroach Node=15434
       1 1091.39 1897.59
Encroach Node=15390
       1 1091.39 1133.59
Encroach Node=15221
       1 1084.13 1159.32
Encroach Node=14316
       1 1046.21 1166.23
Encroach Node=14235
       1 1061.36 1144.81
Encroach Node=13426
       1 1061.36 1624.21
Encroach Node=12617
       1 1532.88 1624.21
Encroach Node=12570
       1 1530.83 1622.52
Encroach Node=11453
       1 1659.74 1760.95
Encroach Node=10309
       1 1662.75 1746.77
Encroach Node=9599
       1 1418.72 1501.04
Encroach Node=9589
       1 1422.72 1505.04
Encroach Node=9579
       1 1402.72 1505.04
Encroach Node=9569
       1 1402.72 1485.04
Encroach Node=9559
       1 1393.72 1476.04
Encroach Node=9229
       1 1398.72 1481.04
Encroach Node=8542
       1 1241.31 1325.86
Encroach Node=8479
       1 1234.31 1318.86
Encroach Node=8394
       1 1231.18 1318.37
Encroach Node=8370
       1 1224.18 1318.37
Encroach Node=8346
       1 1224.18 1311.37
Encroach Node=8258
       1 1224.18 1311.37
Encroach Node=7826
       1 1184.37  1301.2
Encroach Node=7296
       1 1555.82 1686.52
Encroach Node=6869
       1 1609.15 1720.89
Encroach Node=6778
       1 1634.15 1745.89
Encroach Node=6729
       1 1634.15 1765.89
Encroach Node=6680
       1 1654.15 1765.89
Encroach Node=6601
       1 1658.53 1737.69
Encroach Node=6469
       1 1646.54 1737.09
Encroach Node=5677
       1 1690.22 1783.09
Encroach Node=4665
       1  1623.3 1710.44
Encroach Node=4603
       1  1626.3 1713.44
Encroach Node=4577
       1  1621.3 1713.44
Encroach Node=4551
       1  1621.3 1708.44
Encroach Node=4480
       1  1605.3 1692.44
Encroach Node=4416
       1 1152.81 1239.94
Encroach Node=3976
       1 1166.62 1254.58
Encroach Node=3447
       1 1171.81 1262.72
Encroach Node=3348
       1 1159.04 1294.06
Encroach Node=3199
       1 1153.38 1318.47
Encroach Node=3049
       1 1153.38 1318.47
Encroach Node=2860
       1  1192.9 1279.42
Encroach Node=2302
       1  1076.4 1164.38
Encroach Node=1567
       1   381.8  497.05
Encroach Node=1025
       1   513.2  648.17
Encroach Node=956
       1  537.79  646.75
Encroach Node=907
       1  537.79  669.75
Encroach Node=858
       1  560.79  669.75
Encroach Node=791
       1  561.79  670.75
Encroach Node=526
       1  615.68  714.21
Encroach Node=106
       1  767.57  869.04
Encroach Node=95
       1  783.04  856.83
Encroach Node=75
       1  769.29  834.75
Encroach Node=46
       1  761.18  893.34
Computation Interval=1HOUR
Output Interval=1HOUR
Run HTab= 0
Run UNet= 0
Run PostProcess= 0
UNET Theta= 1
UNET ZTol= 0.02
UNET ZSATol= 0.1
UNET MxIter= 20
UNET MaxInSteps= 20
UNET DtIC= 0
UNET DtMin= 0
UNET MaxCRTS= 20
UNET WFStab= 2
UNET SFStab= 1
UNET WFX= 1
UNET SFX= 1
UNET Convert EG Bridges=-1
UNET Use Existing IB Tables=-1
Instantaneous Interval=1HOUR
Write IC File= 0
Write Velocity= 0
Write Detailed= 0

--- D120-00-00.p05 (plan) ---

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Plan Title=Storage Routing
Short Identifier=Store_Rout
Geom File=g01
Flow File=f07

--- D120-00-00.f01 (steady flow) ---

Flow Title=FEMA Effective June 2007
Version=Version 3.0.1  Mar 2001
Number of Profiles= 4
Profile Names=10PCT_10yr,2PCT_50yr,1PCT_100yr,0.2PCT_500yr
River Rch & RM=D120-00-00,D120-00-00_0001 ,15746
     835    1302    1501    2061
River Rch & RM=D120-00-00,D120-00-00_0001 ,14316
    1071    1855    2136    2956
River Rch & RM=D120-00-00,D120-00-00_0001 ,12570
    1147    1955    2247    3093
River Rch & RM=D120-00-00,D120-00-00_0001 ,11453
    1231    2062    2367    3240
River Rch & RM=D120-00-00,D120-00-00_0001 ,10309
    1316    2169    2486    3385
River Rch & RM=D120-00-00,D120-00-00_0001 ,9229
    1397    2270    2598    3521
River Rch & RM=D120-00-00,D120-00-00_0001 ,8258
    1482    2375    2714    3661
River Rch & RM=D120-00-00,D120-00-00_0001 ,7296
    1559    2469    2817    3786
River Rch & RM=D120-00-00,D120-00-00_0001 ,6469
    1637    2562    2921    3909
River Rch & RM=D120-00-00,D120-00-00_0001 ,5677
    1769    2718    3093    4114
River Rch & RM=D120-00-00,D120-00-00_0001 ,4416
    1947    2924    3319    4382
River Rch & RM=D120-00-00,D120-00-00_0001 ,2860
    2108    3106    3520    4618
River Rch & RM=D120-00-00,D120-00-00_0001 ,1567
    2322    3343    3779    4921
Boundary for River Rch & Prof#=D120-00-00,D120-00-00_0001 , 1
Up Type= 0
Dn Type= 3
Dn Slope=.0009
Boundary for River Rch & Prof#=D120-00-00,D120-00-00_0001 , 2
Up Type= 0
Dn Type= 3
Dn Slope=.0009
Boundary for River Rch & Prof#=D120-00-00,D120-00-00_0001 , 3
Up Type= 0
Dn Type= 3
Dn Slope=.0009
Boundary for River Rch & Prof#=D120-00-00,D120-00-00_0001 , 4
Up Type= 0
Dn Type= 3
Dn Slope=.0009
DSS Import GetInterval= 0
DSS Import GetPeak= 0
DSS Import FillOption= 0

--- D120-00-00.f02 (steady flow) ---

Flow Title=Floodway
Version=Version 3.0.1  Mar 2001
Number of Profiles= 2
Profile Names=1PCT_100yr,1PCTFloodway_100yrFW
River Rch & RM=D120-00-00,D120-00-00_0001 ,15746
    1501    1501
River Rch & RM=D120-00-00,D120-00-00_0001 ,14316
    2136    2136
River Rch & RM=D120-00-00,D120-00-00_0001 ,12570
    2247    2247
River Rch & RM=D120-00-00,D120-00-00_0001 ,11453
    2367    2367
River Rch & RM=D120-00-00,D120-00-00_0001 ,10309
    2486    2486
River Rch & RM=D120-00-00,D120-00-00_0001 ,9229
    2598    2598
River Rch & RM=D120-00-00,D120-00-00_0001 ,8258
    2714    2714
River Rch & RM=D120-00-00,D120-00-00_0001 ,7296
    2817    2817
River Rch & RM=D120-00-00,D120-00-00_0001 ,6469
    2921    2921
River Rch & RM=D120-00-00,D120-00-00_0001 ,5677
    3093    3093
River Rch & RM=D120-00-00,D120-00-00_0001 ,4416
    3319    3319
River Rch & RM=D120-00-00,D120-00-00_0001 ,2860
    3520    3520
River Rch & RM=D120-00-00,D120-00-00_0001 ,1567
    3779    3779
Boundary for River Rch & Prof#=D120-00-00,D120-00-00_0001 , 1
Up Type= 0
Dn Type= 1
Dn Known WS=54.13
Boundary for River Rch & Prof#=D120-00-00,D120-00-00_0001 , 2
Up Type= 0
Dn Type= 1
Dn Known WS=55.13
DSS Import GetInterval= 0
DSS Import GetPeak= 0
DSS Import FillOption= 0

--- D120-00-00.f07 (steady flow) ---

Flow Title=Storage Routing
Version=Version 3.0.1  Mar 2001
Number of Profiles= 8
Profile Names=0.1,0.2,0.4,0.6,0.8,1.0,1.2,1.5
River Rch & RM=D120-00-00,D120-00-00_0001 ,15746
     214     428     856    1284    1712    2140    2568    3210
River Rch & RM=D120-00-00,D120-00-00_0001 ,12570
     377     754    1508    2262    3016    3770    4524    5655
Boundary for River Rch & Prof#=D120-00-00,D120-00-00_0001 , 1
Up Type= 0
Dn Type= 3
Dn Slope=.0009
Boundary for River Rch & Prof#=D120-00-00,D120-00-00_0001 , 2
Up Type= 0
Dn Type= 3
Dn Slope=.0009
Boundary for River Rch & Prof#=D120-00-00,D120-00-00_0001 , 3
Up Type= 0
Dn Type= 3
Dn Slope=.0009
Boundary for River Rch & Prof#=D120-00-00,D120-00-00_0001 , 4
Up Type= 0
Dn Type= 3
Dn Slope=.0009
Boundary for River Rch & Prof#=D120-00-00,D120-00-00_0001 , 5
Up Type= 0
Dn Type= 3
Dn Slope=.0009
Boundary for River Rch & Prof#=D120-00-00,D120-00-00_0001 , 6
Up Type= 0
Dn Type= 3
Dn Slope=.0009
Boundary for River Rch & Prof#=D120-00-00,D120-00-00_0001 , 7
Up Type= 0
Dn Type= 3
Dn Slope=.0009
Boundary for River Rch & Prof#=D120-00-00,D120-00-00_0001 , 8
Up Type= 0
Dn Type= 3
Dn Slope=.0009
DSS Import GetInterval= 0
DSS Import GetPeak= 0
DSS Import FillOption= 0

--- D120-00-00.g01 (geometry) ---

Geom Title=D120-00-00 June 2007
Version=Version 3.0.1  Mar 2001

River Reach=D120-00-00      ,D120-00-00_0001
Reach XY= 30
     3048394.666    13811916.405     3049122.477    13811945.036
     3049199.623    13811927.251       3049425.2    13811917.126
     3050384.763    13811963.013     3050420.405    13811975.735
     3050507.087      13812110.8     3050558.964    13812160.636
     3051931.243    13812227.819     3052042.538      13812251.7
     3052199.331    13812238.025     3052310.481     13812124.05
     3052343.437    13812118.495     3053343.201      13812159.2
     3053399.259    13812198.369     3053477.672    13812296.733
     3053534.104    13812328.665     3053690.151    13812329.462
     3053844.484    13812152.418      3053917.45      13812145.3
     3054786.026    13812266.298     3054828.537     13812286.63
     3055888.265    13812417.491     3059266.787    13812577.309
     3061600.672    13812567.138     3061719.024    13812595.011
     3061918.031    13812677.832     3063833.157    13813621.894
     3063966.251    13813715.825     3064036.884    13813746.476

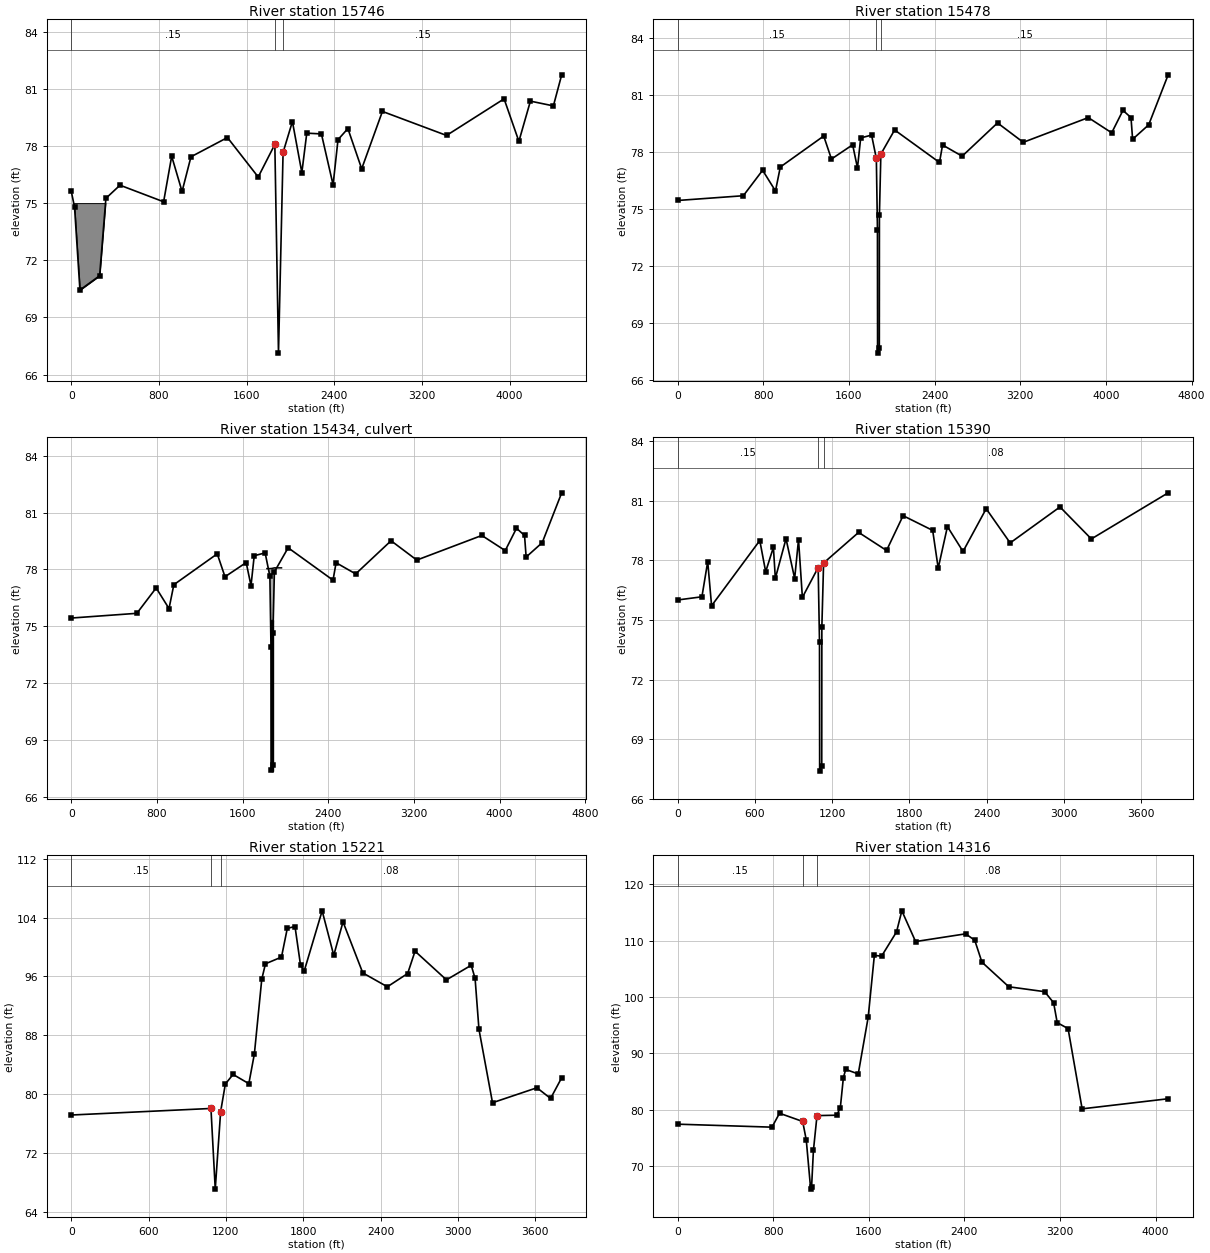
Type RM Length L Ch R = 1 ,15746   ,285.85,268.2,272.67
BEGIN DESCRIPTION:
15746.35--u/s approach Cook Road bridge;  surveyed channel;  blocked obstruction in detention pond
END DESCRIPTION:
XS GIS Cut Line= 5
     3048505.176    13813782.204     3048539.596    13813093.042
     3048896.614     13812006.79     3048917.083    13811888.381
     3048969.424    13809367.046
#Sta/Elev= 30
       0   75.64   30.54   74.79    79.8   70.44  259.41   71.19  316.63   75.25
  445.37   75.94  843.28   75.07  916.91   77.46 1011.64   75.61 1092.83   77.43
 1425.57   78.44 1706.38   76.37 1858.13   78.08 1891.44   67.13 1933.32   77.66
 2018.57   79.28 2104.52    76.6 2149.53   78.67 2283.13   78.63 2389.58   75.96
 2434.59   78.33 2524.61   78.91 2650.59    76.8 2839.68   79.81  3424.8   78.55
 3949.92   80.47 4084.95   78.24 4189.97   80.35 4399.66    80.1 4475.48   81.73
#Mann= 3 , 0 , 0
       0     .15       0 1858.13     .04       0 1933.32     .15       0
#XS Ineff= 2 , 0
       0    1845            1965       0
Permanent Ineff=
       T       T
#Block Obstruct= 1 ,-1
   20.51  335.07      75
Bank Sta=1858.13,1933.32
XS Rating Curve= 0
Exp/Cntr=.5,.3

Type RM Length L Ch R = 1 ,15478   ,86.44,88,87.53
BEGIN DESCRIPTION:
15478.15--u/s face Cook Road bridge;  channel copied from 15390
END DESCRIPTION:
XS GIS Cut Line= 5
     3049094.471    13813820.367      3049122.33    13813057.031
     3049166.584    13811990.128     3049184.292    13811887.303
     3049311.771    13809245.923
#Sta/Elev= 30
       0   75.43  613.28   75.68   793.4   77.02   913.5   75.93  958.54   77.19
 1363.89   78.82 1436.26   77.61 1634.12   78.36 1679.16   77.14 1709.19   78.72
 1811.04   78.87 1855.39   77.64 1865.78   73.89 1866.98    67.4  1883.2   67.66
  1884.1   74.66 1897.59   77.87 2025.91   79.14 2445.07   77.43 2473.72   78.35
 2656.64   77.76 2987.03   79.51 3227.31   78.49 3834.69   79.79 4053.27   78.99
 4158.39   80.17 4233.48   79.79 4248.49   78.65 4398.67   79.41 4580.46   82.04
#Mann= 3 , 0 , 0
       0     .15       0 1855.39     .04       0 1897.59     .15       0
#XS Ineff= 2 , 0
       0    1837            1988       0
Permanent Ineff=
       T       T
Bank Sta=1855.39,1897.59
XS Rating Curve= 0
Exp/Cntr=.5,.3

Type RM Length L Ch R = 2 ,15434   ,,,
BEGIN DESCRIPTION:
Cook Road Box Culvert
END DESCRIPTION:
Bridge Culvert--1,0,-1,-1, 0
Deck Dist Width WeirC Skew NumUp NumDn MinLoCord MaxHiCord MaxSubmerge Is_Ogee
40,40,2.6,0, 5, 5, , , .95, 0, 0,0,,
    1828 1855.39 1874.94 1897.59    1964
   78.04   78.04   78.05   78.08   78.08
                                        
    1070 1091.39 1110.94 1133.59    1200
   78.04   78.04   78.05   78.08   78.08
                                        
BR Coef=-1 , 0 , 0 ,, 0 ,,,.8,-1,2,0,
WSPro=,,,, 1 ,,,, 0 ,,,, 0 ,,,,-1 ,-1 ,-1 , 0 , 0 , 0 , 0 , 0
Multiple Barrel Culv=2,8,8,40,.012,.7,1,8,1,67.35,67.35, 2,Culvert #1  , 0 ,40
 1870.69 1106.69 1879.19 1115.19
Culvert Bottom n=.012
BC Design=,, 0 ,, 0 ,,,,,,

Type RM Length L Ch R = 1 ,15390   ,166.39,169,166.97
BEGIN DESCRIPTION:
15390.15--d/s face Cook Road bridge; surveyed channel
END DESCRIPTION:
XS GIS Cut Line= 5
     3049214.191    13813050.652     3049221.578    13812942.798
     3049251.708    13811980.778     3049269.415    13811877.953
     3049395.348    13809245.923
#Sta/Elev= 30
       0   76.01  188.44   76.17  233.47   77.94  263.48   75.72     638      79
  683.69   77.43  743.72   78.66  758.72    77.1  841.72   79.09   908.8   77.09
  938.81   79.05  968.83   76.14 1091.39   77.64 1101.78   73.89 1102.98    67.4
  1119.2   67.66  1120.1   74.66 1133.59   77.87 1405.65   79.41 1622.59    78.5
 1751.05   80.25 1980.88   79.51 2023.87   77.61 2095.53    79.7 2216.58   78.45
 2396.49    80.6  2582.8   78.88 2969.75   80.69 3213.38   79.08 3809.98    81.4
#Mann= 3 , 0 , 0
       0     .15       0 1091.39     .04       0 1133.59     .08       0
#XS Ineff= 2 , 0
       0    1079            1249       0
Permanent Ineff=
       T       T
Bank Sta=1091.39,1133.59
XS Rating Curve= 0
Exp/Cntr=.5,.3

Type RM Length L Ch R = 1 ,15221   ,929.22,905.05,895.71
BEGIN DESCRIPTION:
15221.15--d/s exit Cook Road bridge; channel copied from 15746
END DESCRIPTION:
XS GIS Cut Line= 5
     3049370.801    13813050.652     3049376.711    13812942.798
     3049417.315      13811995.7     3049435.022    13811892.875
     3049562.502    13809251.495
#Sta/Elev= 30
       0   77.19 1084.13   78.08 1117.44   67.13 1159.32   77.66 1195.74    81.4
 1255.81    82.7 1377.94   81.45 1420.91   85.48 1478.22   95.62 1506.87   97.72
 1631.24   98.63  1676.3  102.53 1736.09  102.78 1779.07   97.52 1807.72   96.75
 1946.61  104.91 2036.72   98.87 2108.57  103.41 2261.98   96.48 2452.39    94.6
 2609.98    96.4 2667.28   99.43 2910.82   95.54 3102.96   97.52 3132.99   95.74
 3163.03   88.82 3268.15   78.86  3612.8   80.89 3718.67   79.44 3804.78   82.25
#Mann= 3 , 0 , 0
       0     .15       0 1084.13     .04       0 1159.32     .08       0
#XS Ineff= 2 , 0
       0    1081            1318       0
Permanent Ineff=
       T       T
Bank Sta=1084.13,1159.32
XS Rating Curve= 0
Exp/Cntr=.3,.1

Type RM Length L Ch R = 1 ,14316   ,109.4,81.09,85.22
BEGIN DESCRIPTION:
14316.10--u/s appraoch Kirkwood box culvert; channel copied from 14235
END DESCRIPTION:
XS GIS Cut Line= 6
     3050260.815    13813080.614     3050302.258    13812341.142
     3050336.079    13812046.901     3050358.332    13809826.028
     3050273.798     13809658.35     3050300.312    13808999.559
#Sta/Elev= 30
       0   77.44  789.59   76.91  852.48   79.38 1046.21   77.92 1076.22   74.65
 1113.27   65.92 1120.98   66.36 1136.22   72.79 1166.23   78.96 1331.24   79.03
 1361.24   80.34 1386.77   85.67 1406.24   87.15 1511.25   86.35 1594.41    96.4
 1646.26  107.39 1706.26  107.23 1831.72  111.54 1876.21  115.28 1991.28  109.83
 2410.15   111.2 2486.31  110.06 2546.32  106.18 2771.33  101.81 3071.35  100.94
 3146.35   98.98 3176.36   95.45 3267.38   94.39 3384.97   80.16 4104.94   81.95
#Mann= 3 , 0 , 0
       0     .15       0 1046.21     .04       0 1166.23     .08       0
#XS Ineff= 2 , 0
       0    1053            1397       0
Permanent Ineff=
       T       T
Bank Sta=1046.21,1166.23
XS Rating Curve= 0
Exp/Cntr=.5,.3

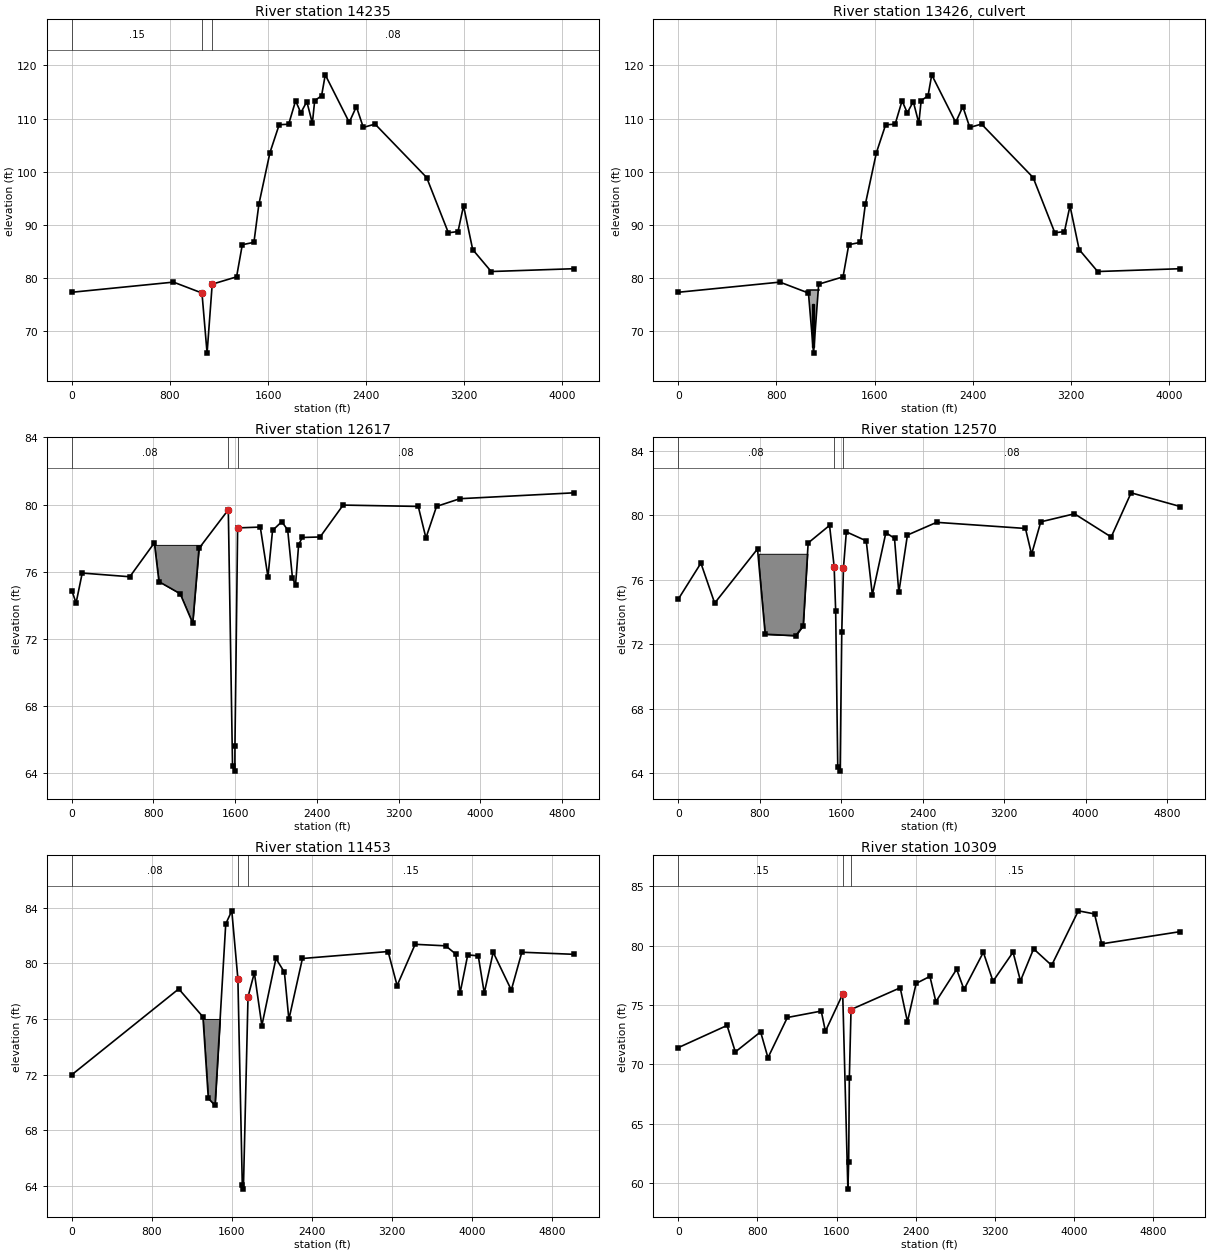
Type RM Length L Ch R = 1 ,14235   ,1565.68,1617.82,1626.69
BEGIN DESCRIPTION:
14235.01--u/s face Kirkwood box culvert;  surveyed channel
END DESCRIPTION:
XS GIS Cut Line= 4
      3050330.71    13813078.818     3050414.936    13812034.564
     3050413.189    13811915.791     3050593.892    13808994.961
#Sta/Elev= 30
       0   77.36  829.13   79.27 1061.36   77.22 1103.02   65.92 1144.81   78.88
 1343.44   80.26 1390.15    86.3 1484.97   86.75 1525.41   93.93 1615.58  103.62
 1690.72  108.86 1768.03  108.95 1824.65  113.36  1867.1   111.1 1916.15   113.2
 1961.24  109.15 1980.33  113.39 2036.38   114.3 2066.44  118.24 2261.81  109.31
    2320  112.26 2376.62  108.35 2472.21  108.98 2893.02   98.93 3070.12   88.54
  3148.5   88.78 3193.59   93.61 3268.26   85.39 3419.02   81.26 4092.85   81.79
#Mann= 3 , 0 , 0
       0     .15       0 1061.36     .04       0 1144.81     .08       0
#XS Ineff= 2 , 0
       0     995            1389       0
Permanent Ineff=
       T       T
Bank Sta=1061.36,1144.81
XS Rating Curve= 0
Exp/Cntr=.5,.3

Type RM Length L Ch R = 2 ,13426   ,,,
BEGIN DESCRIPTION:
Kirkwood Box Culvert
END DESCRIPTION:
Bridge Culvert--1,0,-1,-1, 0
Deck Dist Width WeirC Skew NumUp NumDn MinLoCord MaxHiCord MaxSubmerge Is_Ogee
25,1568,2.6,0, 2, 3, , , .95, 0, 0,0,,
    1050 1144.81
    77.8    77.8
                
 1532.88 1624.21    1653
   79.15   79.15   79.15
                        
BR Coef=-1 , 0 , 0 ,, 0 ,,,.8,-1,2,0,
WSPro=,,,, 1 ,,,, 0 ,,,, 0 ,,,,-1 ,-1 ,-1 , 0 , 0 , 0 , 0 , 0
Multiple Barrel Culv=2,8,8,1568,.012,.7,1,8,1,67.1,65.6, 2,Culvert #1  , 0 ,25
 1097.41 1580.71 1106.41 1589.71
Culvert Bottom n=.012
BC Design=,, 0 ,, 0 ,,,,,,

Type RM Length L Ch R = 1 ,12617   ,46.09,46.87,45.68
BEGIN DESCRIPTION:
12617.18--d/s face Kirkwood box culvert; surveyed channel; blocked obstruction in detention pond
END DESCRIPTION:
XS GIS Cut Line= 6
     3051840.325    13813834.678     3051898.378    13812859.013
     3051922.723    13812699.835     3051935.319    13812319.718
     3051939.017    13812028.318     3052097.483    13808925.904
#Sta/Elev= 30
       0   74.88   42.28   74.14  102.42   75.92  568.28    75.7  808.66   77.72
  853.73   75.41 1061.32   74.69 1184.07   72.94 1245.84   77.39 1532.88   79.69
 1574.34    64.4 1597.25   64.12  1597.9   65.63 1624.21   78.61 1846.08   78.66
 1921.17   75.69 1966.23   78.46 2056.35   78.98 2114.39   78.49 2161.49   75.61
 2191.53   75.23 2221.56   77.61 2257.29   78.04 2431.84   78.07 2657.13   79.97
 3393.09   79.89 3468.19   78.01 3571.94   79.89 3800.57   80.35 4916.67    80.7
#Mann= 3 , 0 , 0
       0     .08       0 1532.88     .04       0 1624.21     .08       0
#XS Ineff= 2 , 0
       0    1516            1786       0
Permanent Ineff=
       T       T
#Block Obstruct= 1 ,-1
  796.61 1331.99    77.6
Bank Sta=1532.88,1624.21
XS Rating Curve= 0
Exp/Cntr=.5,.3

Type RM Length L Ch R = 1 ,12570   ,1113.44,1117.79,1108.24
BEGIN DESCRIPTION:
12570.31--d/s exit Kirkwood box culvert; channel copied from 12617; blocked obstruction in detention pond
END DESCRIPTION:
XS GIS Cut Line= 6
     3051889.015    13813834.678     3051943.866    13812861.574
     3051968.211    13812702.396     3051980.807    13812322.279
     3051984.505    13812030.879     3052192.366    13808915.361
#Sta/Elev= 30
       0   74.78  222.59   77.02   357.8   74.54  778.46    77.9  853.58   72.61
 1154.31   72.52 1226.94   73.14  1275.7   78.27 1485.81   79.36 1530.83   76.81
 1545.83   74.06 1566.34    64.4 1589.25   64.12 1605.83   72.75 1622.52   76.74
 1650.83   78.96 1845.96    78.4 1906.09   75.05 2038.97   78.91 2123.53   78.56
 2165.81    75.2 2250.37   78.76 2537.49   79.55 3409.43   79.17 3469.56   77.57
 3559.76   79.58  3890.5   80.08  4251.3   78.64 4446.73   81.38 4929.94   80.53
#Mann= 3 , 0 , 0
       0     .08       0 1530.83     .04       0 1622.52     .08       0
#XS Ineff= 2 , 0
       0    1496            1782       0
Permanent Ineff=
       T       T
#Block Obstruct= 1 ,-1
  791.02 1276.45    77.6
Bank Sta=1530.83,1622.52
XS Rating Curve= 0
Exp/Cntr=.3,.1

Type RM Length L Ch R = 1 ,11453   ,1106.56,1143.68,1045.59
BEGIN DESCRIPTION:
11452.52--blocked obstruction in detention pond
END DESCRIPTION:
XS GIS Cut Line= 4
     3052840.013    13813863.826     3053044.423    13812239.634
     3053045.323    13812100.368      3053189.41     13808863.37
#Sta/Elev= 30
       0   71.98 1068.73   78.16 1310.44   76.15 1364.15   70.29 1431.29   69.77
 1538.37   82.84 1598.84   83.78 1659.74   78.89  1703.7   64.05 1714.86   63.75
 1760.95   77.59 1824.19   79.32 1899.26   75.52 2039.86   80.35 2124.49   79.36
 2169.23   75.96 2304.66   80.35 3160.51   80.85  3250.6    78.4 3430.78   81.37
 3736.11   81.26 3836.18   80.67 3879.86   77.86  3956.3   80.61  4061.4   80.54
 4121.46   77.86 4210.48    80.8 4391.73   78.08 4496.83    80.8 5016.47   80.65
#Mann= 3 , 0 , 0
       0     .08       0 1659.74     .04       0 1760.95     .15       0
#XS Ineff= 2 , 0
       0    1321            1790       0
Permanent Ineff=
       T       T
#Block Obstruct= 1 ,-1
    1307 1487.95      76
Bank Sta=1659.74,1760.95
XS Rating Curve= 0
Exp/Cntr=.3,.1

Type RM Length L Ch R = 1 ,10309   ,721.66,709.39,718.73
BEGIN DESCRIPTION:
 10308.85--surveyed channel
END DESCRIPTION:
XS GIS Cut Line= 5
     3053839.527    13813873.979     3053900.071    13812751.179
     3054019.208    13812244.742      3054041.76    13812117.295
      3054119.75    13808817.116
#Sta/Elev= 30
       0    71.4  493.59   73.27  577.32   71.04  832.69   72.73  906.93   70.55
 1103.08   73.94 1445.54   74.48 1487.77   72.78 1662.75   75.91 1714.82   59.49
 1722.88   61.79 1729.58   68.82 1746.77   74.61 2243.69   76.44 2316.98   73.58
 2404.93   76.81 2544.13    77.4 2604.15   75.27 2814.21      78 2888.64    76.3
 3084.28   79.43 3181.79   76.99 3384.36   79.44 3459.39   77.02 3592.21   79.72
 3774.47   78.33 4044.55   82.92 4207.84   82.66 4281.13   80.14 5075.22   81.17
#Mann= 3 , 0 , 0
       0     .15       0 1662.75     .04       0 1746.77     .15       0
#XS Ineff= 2 , 0
       0    1475            1791       0
Permanent Ineff=
       T       T
Bank Sta=1662.75,1746.77
XS Rating Curve= 0
Exp/Cntr=.3,.1

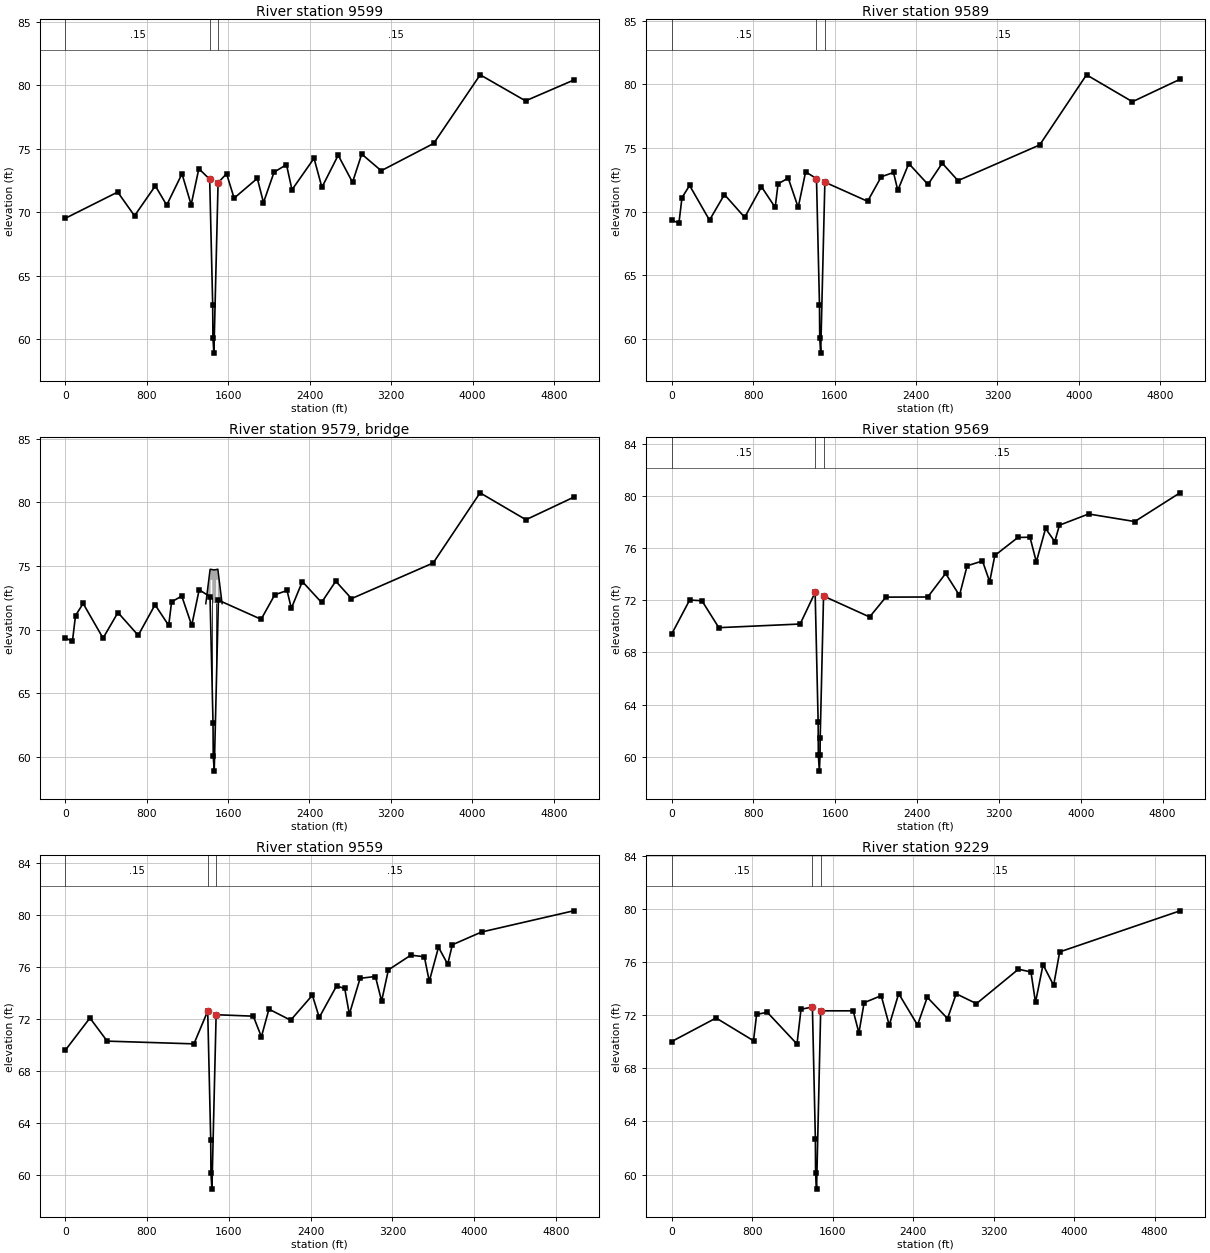
Type RM Length L Ch R = 1 ,9599    ,11.21,10.03,10.24
BEGIN DESCRIPTION:
9599.456--u/s appraoch Leawood pedestrian bridge; channel copied from 9229
END DESCRIPTION:
XS GIS Cut Line= 5
     3054628.517    13813736.582     3054726.167    13812309.557
     3054746.453    13812192.299     3054855.699    13811250.052
     3055023.598    13808762.438
#Sta/Elev= 30
       0   69.52  515.28   71.59  680.67   69.72  884.73   72.08  996.41   70.56
 1146.76   73.03 1236.53   70.59 1312.14   73.43 1418.72    72.6 1448.24   62.66
 1450.27   60.13 1459.93   58.91 1501.04   72.32 1584.39   73.04 1658.38   71.11
  1886.4   72.67 1946.81   70.76  2050.8   73.16 2172.58   73.75 2226.71   71.77
 2443.21   74.25 2520.53   71.96  2680.4   74.49 2821.21   72.36 2911.41   74.58
 3102.91   73.27 3618.02   75.42 4074.68   80.82 4520.06   78.77  4991.2    80.4
#Mann= 3 , 0 , 0
       0     .15       0 1418.72     .04       0 1501.04     .15       0
#XS Ineff= 2 , 0
       0    1233            1535       0
Permanent Ineff=
       T       T
Bank Sta=1418.72,1501.04
XS Rating Curve= 0
Exp/Cntr=.5,.3

Type RM Length L Ch R = 1 ,9589    ,22.98,20.06,21.93
BEGIN DESCRIPTION:
9589.428--u/s face Leawood pedestrian bridge; channel copied from 9229
END DESCRIPTION:
XS GIS Cut Line= 5
      3054658.22    13813743.633     3054735.969    13812311.567
     3054756.255    13812194.309     3054874.217    13811208.078
     3055039.647    13808766.141
#Sta/Elev= 30
       0   69.34   71.24   69.11  101.28   71.11  176.12   72.06  371.68   69.34
  518.09   71.35  717.19   69.56  882.43   71.96 1016.79   70.34 1045.28   72.19
 1145.02   72.64 1242.96   70.34 1316.01   73.13 1422.72    72.6 1452.24   62.66
 1454.27   60.13 1463.93   58.91 1505.04   72.32 1924.73   70.82 2058.56   72.74
 2179.42   73.08 2221.58   71.68 2329.52   73.78 2518.42   72.14 2658.01   73.81
 2812.62   72.44 3615.48   75.24 4075.51   80.74 4526.54   78.63 4993.97   80.39
#Mann= 3 , 0 , 0
       0     .15       0 1422.72     .04       0 1505.04     .15       0
#XS Ineff= 2 , 0
       0    1238            1539       0
Permanent Ineff=
       T       T
Bank Sta=1422.72,1505.04
XS Rating Curve= 0
Exp/Cntr=.5,.3

Type RM Length L Ch R = 3 ,9579    ,,,
BEGIN DESCRIPTION:
Leawood Pedestrian Bridge
END DESCRIPTION:
Bridge Culvert--1,0,-1,-1, 0
Deck Dist Width WeirC Skew NumUp NumDn MinLoCord MaxHiCord MaxSubmerge Is_Ogee
5,10,2.6,0, 12, 12, , , .95, 0, 0,0,,
 1381.22 1423.28 1428.28 1428.38 1444.38 1444.38 1461.38 1483.38 1483.38 1499.38
 1499.48 1541.54
   72.04   74.74   74.74   74.74   74.72   74.72   74.69   74.72   74.72   74.75
   74.75   72.05
                           73.92   73.92   72.09   72.09   72.09   73.92   73.92
                
 1361.22 1403.28 1408.28 1408.38 1424.38 1424.38 1441.38 1463.38 1463.38 1479.38
 1479.48 1521.54
   72.04   74.74   74.74   74.74   74.72   74.72   74.69   74.72   74.72   74.75
   74.75   72.05
                           73.92   73.92   72.09   72.09   72.09   73.92   73.92
                
Pier Skew, UpSta & Num, DnSta & Num=  ,1444.38, 2 ,1424.38, 2 , 0 , 0 , 0 ,,
       1       1
      50    72.6
       1       1
      50    72.6
Pier Skew, UpSta & Num, DnSta & Num=  ,1483.38, 2 ,1463.38, 2 , 0 , 0 , 0 ,,
       1       1
    49.6    72.2
       1       1
    49.6    72.2
BR Coef=-1 , 1 , 1 ,1.25, 0 ,,,.8,-1,2,0,
WSPro=,,,, 1 ,,,, 0 ,,,, 0 ,,,,-1 ,-1 ,-1 , 0 , 0 , 0 , 0 , 0
BC Design=,, 0 ,, 0 ,,,,,,

Type RM Length L Ch R = 1 ,9569    ,11.31,10.01,10.62
BEGIN DESCRIPTION:
9569.372--d/s face Leawood pedestrian bridge; channel copied from 9229
END DESCRIPTION:
XS GIS Cut Line= 5
     3054728.365    13813728.467     3054755.571    13812315.597
     3054775.857    13812198.339     3054916.192    13811240.176
      3055084.09    13808776.018
#Sta/Elev= 30
       0   69.41     176   72.02  296.02   71.96  461.05    69.9  1256.2   70.18
 1402.72    72.6 1432.24   62.66 1434.27   60.13 1443.93   58.91 1451.06   60.13
 1452.13   61.44 1485.04   72.32 1935.43   70.72 2094.11   72.24 2504.26   72.25
 2678.61   74.05 2813.92   72.37 2889.09   74.64 3039.13   75.01 3109.51   73.42
 3159.72   75.43 3385.24   76.81 3503.63   76.83 3565.66   74.94 3655.87    77.5
 3746.07   76.49 3791.18   77.75 4076.84   78.61 4527.89   78.03 4970.39   80.23
#Mann= 3 , 0 , 0
       0     .15       0 1402.72     .04       0 1485.04     .15       0
#XS Ineff= 2 , 0
       0    1217            1518       0
Permanent Ineff=
       T       T
Bank Sta=1402.72,1485.04
XS Rating Curve= 0
Exp/Cntr=.5,.3

Type RM Length L Ch R = 1 ,9559    ,309.29,330.75,341.15
BEGIN DESCRIPTION:
9559.362--d/s exit Leawood pedestrian bridge; channel copied from 9229
END DESCRIPTION:
XS GIS Cut Line= 5
     3054741.635     13813722.78     3054766.792    13812309.307
     3054787.078    13812192.049     3054931.006    13811251.287
     3055098.905    13808769.845
#Sta/Elev= 30
       0   69.58  241.88   72.07  410.34   70.29 1258.94   70.08 1393.72    72.6
 1423.24   62.66 1425.27   60.13 1434.93   58.91 1476.04   72.32 1839.76   72.21
 1918.73   70.62 1992.53   72.75 2204.98    71.9 2417.42   73.82  2484.4   72.11
 2653.65   74.53 2733.76   74.34 2778.86   72.36  2884.1   75.12 3033.85   75.26
 3094.58   73.37 3160.58   75.77 3380.24    76.9 3512.62   76.78 3560.65   74.89
 3650.85   77.51 3741.06    76.2 3786.16    77.7 4071.81   78.68 4971.52   80.31
#Mann= 3 , 0 , 0
       0     .15       0 1393.72     .04       0 1476.04     .15       0
#XS Ineff= 2 , 0
       0    1210            1511       0
Permanent Ineff=
       T       T
Bank Sta=1393.72,1476.04
XS Rating Curve= 0
Exp/Cntr=.3,.1

Type RM Length L Ch R = 1 ,9229    ,692.38,686.23,677.6
BEGIN DESCRIPTION:
 9228.608--surveyed channel
END DESCRIPTION:
XS GIS Cut Line= 5
     3054759.426    13813727.698     3055086.302    13812386.865
     3055106.588    13812269.608     3055379.387    13811330.375
     3055492.642    13808757.732
#Sta/Elev= 30
       0   70.01  441.31   71.78  813.34   70.07  844.22   72.05  950.24   72.21
 1245.64   69.82  1285.4   72.44 1398.72    72.6 1428.24   62.66 1430.27   60.13
 1439.93   58.91 1481.04   72.32 1804.14   72.32 1860.89   70.66 1912.62   72.93
 2082.54   73.46 2162.54   71.24 2256.26   73.61  2443.7   71.25 2540.41   73.34
 2741.75   71.74 2828.04    73.6 3029.38   72.86 3446.44   75.45 3571.08   75.24
 3616.13   72.95 3690.93   75.79  3796.3   74.24 3856.36   76.75 5052.28   79.84
#Mann= 3 , 0 , 0
       0     .15       0 1398.72     .04       0 1481.04     .15       0
#XS Ineff= 2 , 0
       0    1205            1545       0
Permanent Ineff=
       T       T
Bank Sta=1398.72,1481.04
XS Rating Curve= 0
Exp/Cntr=.3,.1

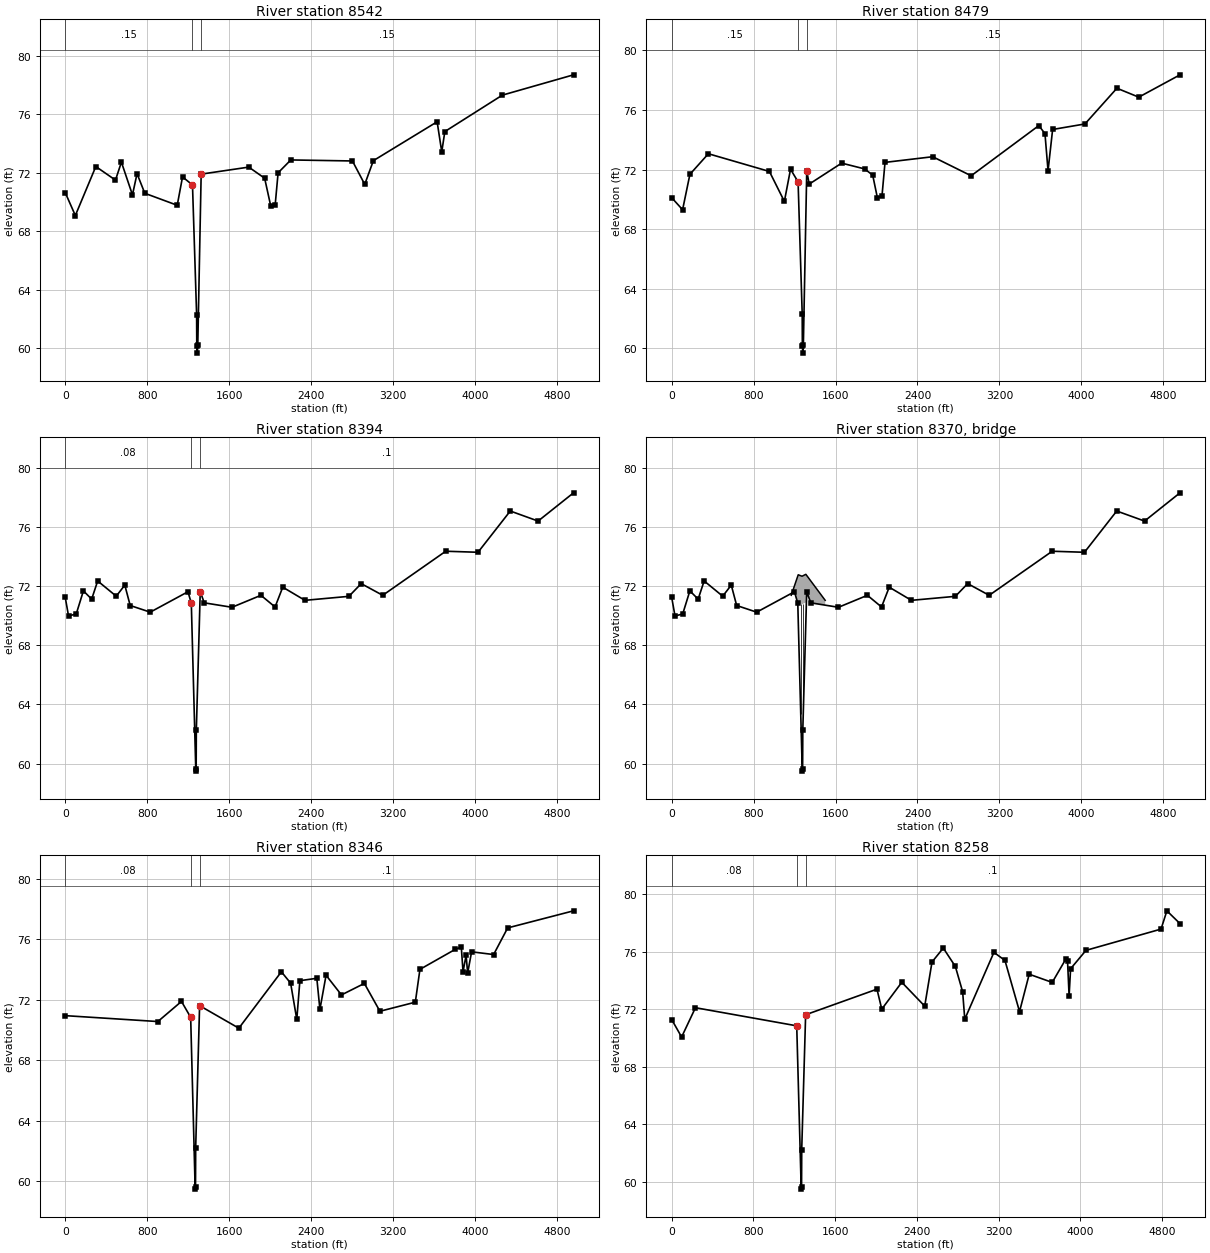
Type RM Length L Ch R = 1 ,8542    ,63.7,63.56,57.15
BEGIN DESCRIPTION:
 8542.379--surveyed channel
END DESCRIPTION:
XS GIS Cut Line= 5
     3055657.874    13813695.935     3055762.885    13812476.397
      3055784.05    13812357.399     3055867.555    13812007.051
     3056033.022    13808759.038
#Sta/Elev= 30
       0   70.65    98.8   69.08  298.55   72.43  490.24    71.5  548.06   72.73
  655.85   70.49  700.54   71.94   776.3    70.6 1092.46   69.78 1144.12   71.72
 1241.31   71.17 1281.48   62.31 1283.12   60.14 1288.05   59.67 1292.75    60.2
 1325.86   71.91 1790.35   72.39 1944.94   71.63 2004.72   69.72 2047.59    69.8
 2076.17      72 2200.27   72.88 2801.05   72.81  2921.2   71.21 3005.12   72.83
 3627.12   75.49 3672.18   73.43 3702.22   74.82 4262.76   77.31  4957.3    78.7
#Mann= 3 , 0 , 0
       0     .15       0 1241.31     .04       0 1325.86     .15       0
#XS Ineff= 2 , 0
       0     991            1448       0
Permanent Ineff=
       T       T
Bank Sta=1241.31,1325.86
XS Rating Curve= 0
Exp/Cntr=.3,.1

Type RM Length L Ch R = 1 ,8479    ,115.03,84.53,59.44
BEGIN DESCRIPTION:
8478.818--u/s appraoch Boone Road bridge; channel copied from 8542
END DESCRIPTION:
XS GIS Cut Line= 5
     3055721.023    13813703.779     3055826.034    13812484.242
     3055847.199    13812365.243     3055907.169    13812012.633
     3056061.687    13808755.455
#Sta/Elev= 30
       0   70.11  106.67    69.3  178.13   71.68  358.34   73.06   954.4   71.87
 1100.34   69.86 1160.56   72.02 1234.31   71.17 1274.48   62.31 1276.12   60.14
 1281.05   59.67 1285.75    60.2 1318.86   71.91 1342.62   71.02 1659.65   72.43
 1884.63   72.04 1963.02   71.62 2008.07   70.12 2053.12   70.19 2083.15   72.48
 2548.67   72.86 2924.09   71.58 3584.84   74.95  3644.9   74.41 3674.94   71.92
 3719.73   74.69 4035.14   75.06 4347.48   77.46 4560.93   76.86 4963.43   78.36
#Mann= 3 , 0 , 0
       0     .15       0 1234.31     .04       0 1318.86     .15       0
#XS Ineff= 2 , 0
       0     973            1478       0
Permanent Ineff=
       T       T
Bank Sta=1234.31,1318.86
XS Rating Curve= 0
Exp/Cntr=.5,.3

Type RM Length L Ch R = 1 ,8394    ,48.42,48.43,51.09
BEGIN DESCRIPTION:
8394.284--u/s face Boone Road bridge; channel copied from 8346
END DESCRIPTION:
XS GIS Cut Line= 5
     3055843.917     13813705.01     3055938.714    13812510.281
     3055917.231     13812385.02     3055967.234    13811346.148
     3056093.936    13808751.872
#Sta/Elev= 30
       0   71.25   32.61   69.98  107.85   70.12   177.6   71.68  258.32   71.12
  317.01   72.35  498.24   71.32  581.89   72.07   634.5   70.69  830.11   70.24
 1198.48   71.62 1231.18   70.85 1275.19   59.49 1278.45   59.63 1280.12   62.24
 1318.37   71.62 1358.13   70.87 1628.44   70.57  1910.9   71.38 2048.93   70.59
 2124.02   71.93 2340.73   71.04 2769.78   71.31 2889.92   72.17 3100.17   71.38
 3715.33   74.36 4030.34   74.29 4345.35   77.08 4616.98    76.4 4963.02   78.31
#Mann= 3 , 0 , 0
       0     .08       0 1231.18     .04       0 1318.37      .1       0
#XS Ineff= 2 , 0
       0     921            1500       0
Permanent Ineff=
       T       T
Bank Sta=1231.18,1318.37
XS Rating Curve= 0
Exp/Cntr=.5,.3

Type RM Length L Ch R = 3 ,8370    ,,,
BEGIN DESCRIPTION:
Boone Road Bridge
END DESCRIPTION:
Bridge Culvert--1,0,-1,-1, 0
Deck Dist Width WeirC Skew NumUp NumDn MinLoCord MaxHiCord MaxSubmerge Is_Ogee
4,40,2.6,0, 7, 7, , , .95, 0, 0,0,,
 1167.41 1235.53 1235.53 1272.78 1310.03 1310.03 1498.96
   71.38   72.77   72.77   72.67    72.8    72.8   71.04
                   70.87   70.77    70.9
 1160.41 1228.53 1228.53 1265.78 1303.03 1303.03 1491.96
   71.38   72.77   72.77   72.67    72.8    72.8   71.04
                   70.87   70.77    70.9
Pier Skew, UpSta & Num, DnSta & Num=  ,1260.33, 2 ,1253.33, 2 , 0 , 0 , 0 ,,
    1.35    1.35
      55    71.3
    1.35    1.35
      55    71.3
Pier Skew, UpSta & Num, DnSta & Num=  ,1285.23, 2 ,1278.23, 2 , 0 , 0 , 0 ,,
    1.35    1.35
      55    71.3
    1.35    1.35
      55    71.3
BR Coef=-1 , 1 , 1 ,1.25, 0 ,,,.8,-1,2,0,
WSPro=,,,, 1 ,,,, 0 ,,,, 0 ,,,,-1 ,-1 ,-1 , 0 , 0 , 0 , 0 , 0
BC Design=,, 0 ,, 0 ,,,,,,

Type RM Length L Ch R = 1 ,8346    ,84.72,87.88,87.95
BEGIN DESCRIPTION:
8345.856--d/s face Boone Road bridge; surveyed channel
END DESCRIPTION:
XS GIS Cut Line= 5
     3055916.519     13813705.01     3055986.177    13812507.533
     3055964.695    13812382.273     3056052.957    13811345.431
     3056176.349    13808755.455
#Sta/Elev= 30
       0   70.96  904.04   70.57 1134.52    71.9 1224.18   70.85 1268.19   59.49
 1271.45   59.63 1273.12   62.24 1311.37   71.62  1694.3   70.13 2109.18   73.86
 2199.51   73.11 2259.73   70.71 2289.83   73.27 2455.21   73.43 2485.25   71.37
 2545.31   73.63 2695.48   72.33 2919.02   73.09 3070.91   71.25  3416.3   71.85
 3461.35   74.02 3807.73   75.35 3865.07   75.49 3881.83   73.86 3911.86   74.95
 3926.88   73.77 3965.41   75.18 4180.42      75 4317.32   76.76 4960.09   77.89
#Mann= 3 , 0 , 0
       0     .08       0 1224.18     .04       0 1311.37      .1       0
#XS Ineff= 2 , 0
       0     899            1523       0
Permanent Ineff=
       T       T
Bank Sta=1224.18,1311.37
XS Rating Curve= 0
Exp/Cntr=.5,.3

Type RM Length L Ch R = 1 ,8258    ,419.12,431.88,440.21
BEGIN DESCRIPTION:
8257.981--d/s exit Boone Road bridge; channel copied from 8346
END DESCRIPTION:
XS GIS Cut Line= 5
     3055980.045    13813709.547     3056072.524     13812503.83
     3056051.042    13812378.569     3056163.855    13811345.117
     3056298.177    13808748.289
#Sta/Elev= 30
       0   71.29   97.33   70.07  232.73   72.11 1224.18   70.85 1268.19   59.49
 1271.45   59.63 1273.12   62.24 1311.37   71.62 2009.77    73.4 2056.67   72.01
 2252.83   73.88 2477.11   72.22 2548.52   75.29 2658.93   76.26 2777.02   74.98
 2848.42   73.22 2869.21   71.31 3154.59   75.96 3262.58    75.4  3405.4   71.84
 3500.06   74.44 3725.36   73.87 3860.54   75.52 3875.56   75.33 3890.58   72.93
 3905.24   74.82  4055.8    76.1 4790.69   77.58 4847.81   78.85 4976.24   77.96
#Mann= 3 , 0 , 0
       0     .08       0 1224.18     .04       0 1311.37      .1       0
#XS Ineff= 2 , 0
       0     887            1563       0
Permanent Ineff=
       T       T
Bank Sta=1224.18,1311.37
XS Rating Curve= 0
Exp/Cntr=.3,.1