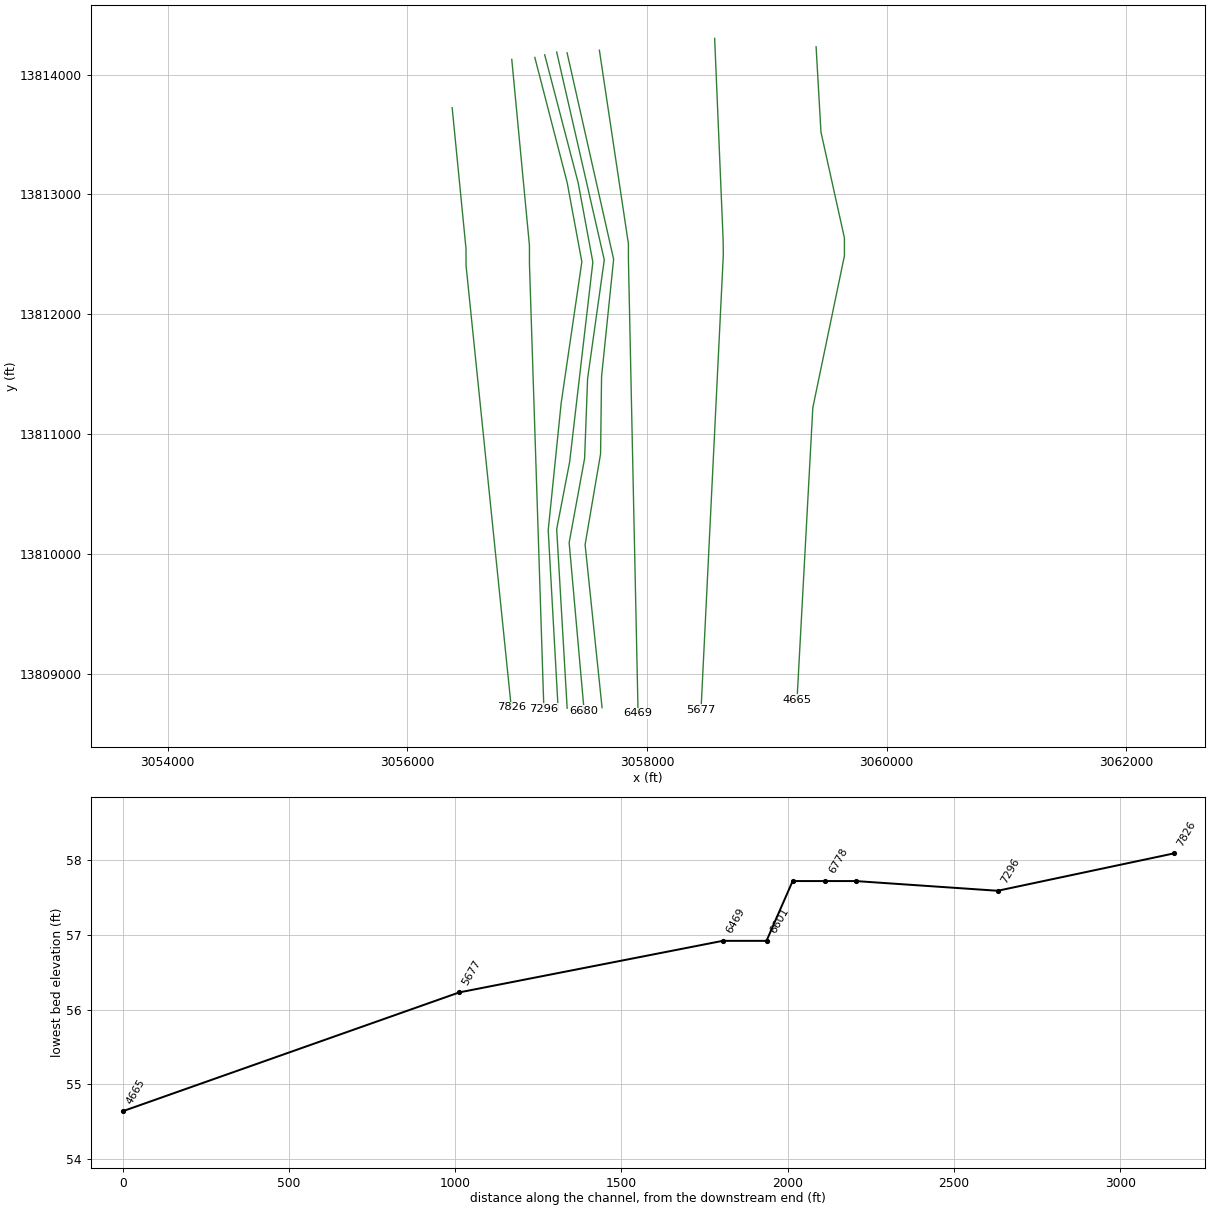
HEC-RAS study D120-00-00.prj: D120-00-00

--- D120-00-00.g01 (geometry) --- (continued)

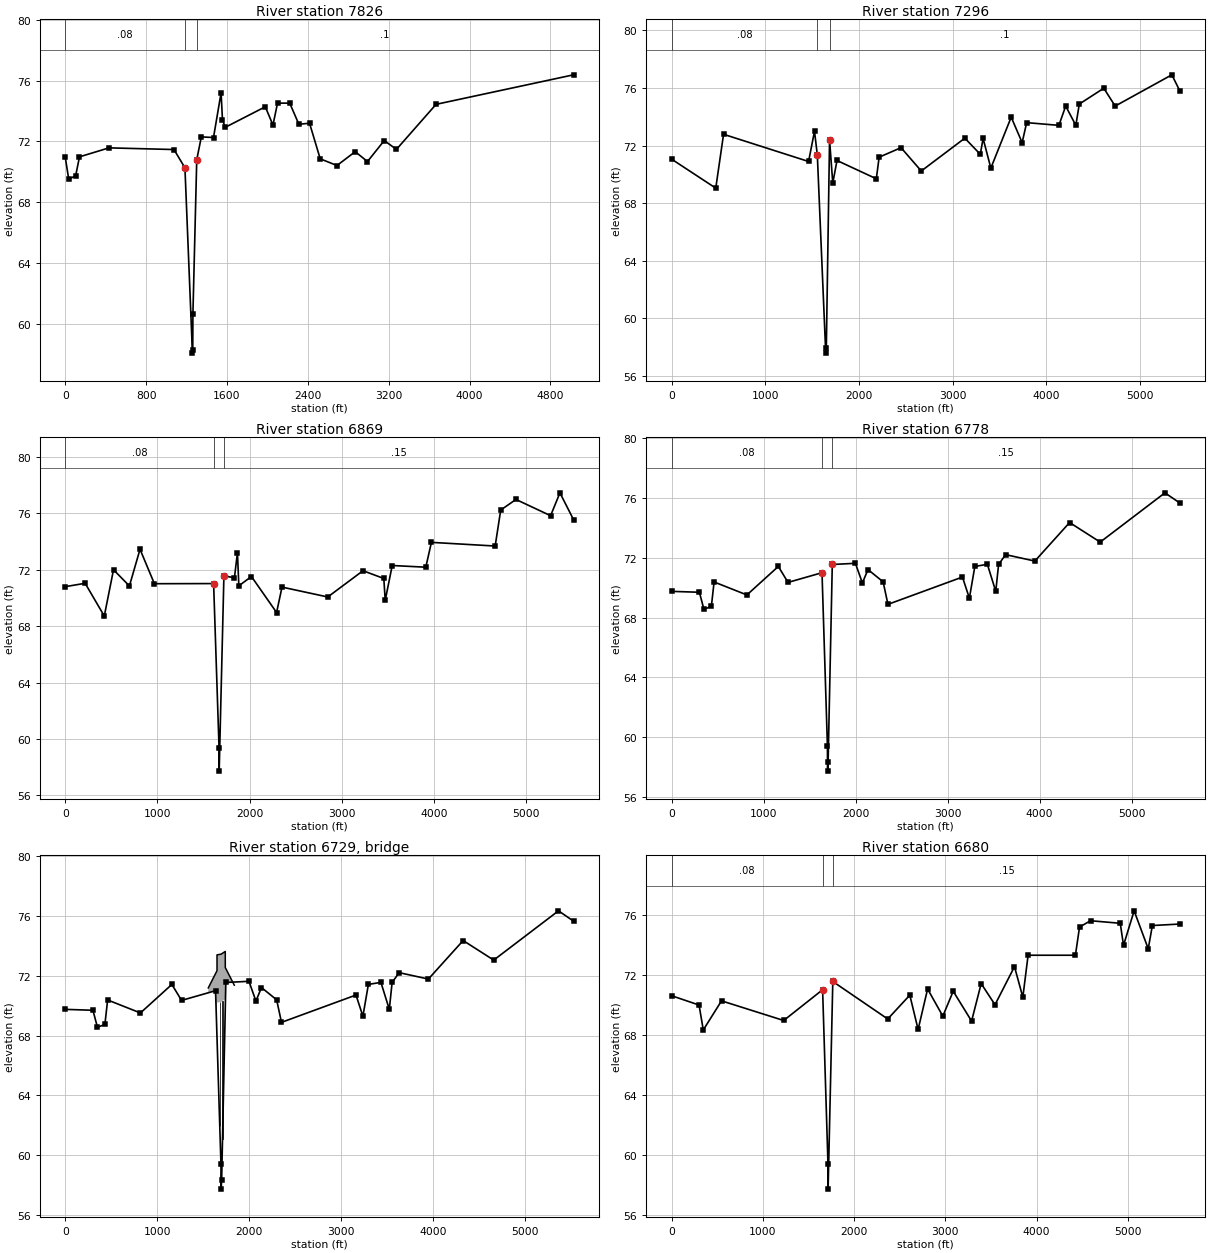
Type RM Length L Ch R = 1 ,7826    ,530.39,529.97,522.55
BEGIN DESCRIPTION:
 7826.106--surveyed channel
END DESCRIPTION:
XS GIS Cut Line= 4
     3056374.818     13813723.16     3056490.531    13812544.455
     3056490.531    13812407.447     3056867.904    13808719.623
#Sta/Elev= 30
       0   70.98   35.08   69.51  103.71   69.76  141.34   70.99   433.1   71.58
 1075.81   71.47 1184.37   70.27 1258.58   58.09  1261.6   58.27 1263.28   60.67
  1301.2    70.8 1346.46    72.3 1467.08   72.26 1541.98    75.2 1555.66   73.43
 1583.02   72.93 1979.24   74.28 2055.14   73.08 2100.37   74.52    2221   74.52
 2311.47   73.13 2417.02    73.2 2522.57   70.86 2688.43   70.42 2868.81   71.33
    2990   70.68 3155.86   72.06 3276.48   71.48 3668.52   74.44 5028.46   76.38
#Mann= 3 , 0 , 0
       0     .08       0 1184.37     .04       0  1301.2      .1       0
#XS Ineff= 2 , 0
       0     854            1549       0
Permanent Ineff=
       T       T
Bank Sta=1184.37,1301.2
XS Rating Curve= 0
Exp/Cntr=.3,.1

Type RM Length L Ch R = 1 ,7296    ,409.7,427.08,422.19
BEGIN DESCRIPTION:
 7296.14--surveyed channel
END DESCRIPTION:
XS GIS Cut Line= 4
     3056872.258    13814126.351     3057019.793     13812572.67
     3057019.793    13812420.505     3057140.226    13808705.291
#Sta/Elev= 30
       0   71.06  470.96   69.05  554.19   72.79  1462.4    70.9 1525.68      73
 1555.82   71.36 1645.77   57.59 1652.01   57.97 1686.52    72.4 1720.84    69.4
 1765.87   70.97 2186.09    69.7  2216.1    71.2 2450.05   71.86 2666.34   70.24
 3131.59   72.52 3296.67    71.4 3326.69    72.5 3409.47   70.44 3626.85   73.98
 3743.81   72.21 3791.93    73.6  4136.3   73.41 4208.98   74.75 4317.21   73.41
 4354.35   74.89 4616.01   75.99 4737.43   74.75 5342.84   76.92    5430   75.78
#Mann= 3 , 0 , 0
       0     .08       0 1555.82     .04       0 1686.52      .1       0
#XS Ineff= 2 , 0
       0    1221            1736       0
Permanent Ineff=
       T       T
Bank Sta=1555.82,1686.52
XS Rating Curve= 0
Exp/Cntr=.3,.1

Type RM Length L Ch R = 1 ,6869    ,91.04,90.78,92.98
BEGIN DESCRIPTION:
6869.056--u/s approach Wilcrest bridge; channel copied from 6680
END DESCRIPTION:
XS GIS Cut Line= 6
     3057064.667    13814142.844      3057334.57    13813098.532
     3057457.124     13812436.92     3057284.582    13811258.451
     3057176.382    13810197.267     3057259.613    13808699.125
#Sta/Elev= 30
       0   70.79     216   71.03  423.83   68.71  523.78   71.99  696.13   70.84
  811.15   73.44  966.97      71 1609.15   71.01 1668.12   59.37 1669.46   57.72
 1720.89   71.56  1834.9   71.42 1867.51    73.2 1882.68   70.85  2019.2   71.51
 2292.06   68.96 2350.69   70.76 2846.97   70.06 3228.97   71.92 3454.66   71.37
 3469.83   69.82  3545.7   72.29 3909.88   72.17 3970.57   73.93 4662.04   73.67
 4722.13   76.22 4887.39   76.97 5262.97   75.82 5364.19   77.44 5511.73   75.54
#Mann= 3 , 0 , 0
       0     .08       0 1609.15     .04       0 1720.89     .15       0
#XS Ineff= 2 , 0
       0    1492            1818       0
Permanent Ineff=
       T       T
Bank Sta=1609.15,1720.89
XS Rating Curve= 0
Exp/Cntr=.5,.3

Type RM Length L Ch R = 1 ,6778    ,97.43,98.65,93.33
BEGIN DESCRIPTION:
6778.278--u/s face Wilcrest bridge; channel copied from 6680
END DESCRIPTION:
XS GIS Cut Line= 6
     3057147.127    13814164.833     3057426.427    13813096.053
     3057548.981     13812434.44     3057355.327    13810767.393
     3057247.128     13810205.59      3057334.52    13808711.609
#Sta/Elev= 30
       0   69.76  301.31    69.7  350.48   68.56  431.35   68.75   461.1   70.39
  817.56   69.52 1159.41   71.43 1264.63   70.36 1634.15   71.01 1693.12   59.37
 1694.46   57.72 1700.42   58.31 1745.89   71.56 1997.23   71.64 2073.08   70.32
 2133.68   71.22 2298.34    70.4 2350.89   68.89 3160.78   70.72 3236.02    69.3
 3295.43   71.43 3431.65   71.57 3522.92   69.76 3553.48   71.56 3629.72   72.22
 3947.68   71.79 4325.61   74.37 4658.13   73.06 5361.87   76.36  5525.5   75.67
#Mann= 3 , 0 , 0
       0     .08       0 1634.15     .04       0 1745.89     .15       0
#XS Ineff= 2 , 0
       0    1577            1822       0
Permanent Ineff=
       T       T
Bank Sta=1634.15,1745.89
XS Rating Curve= 0
Exp/Cntr=.5,.3

Type RM Length L Ch R = 3 ,6729    ,,,
BEGIN DESCRIPTION:
Wilcrest Bridge (modeled as one bridge)
END DESCRIPTION:
Bridge Culvert--1,0,-1,-1, 0
Deck Dist Width WeirC Skew NumUp NumDn MinLoCord MaxHiCord MaxSubmerge Is_Ogee
14,70,2.6,0, 7, 7, , , .95, 0, 0,0,,
 1555.33 1650.02 1650.02 1695.02 1740.02 1740.12 1837.92
    71.2   72.35   73.41   73.46   73.64   72.56   71.38
                   70.21   70.26   70.44
 1575.33 1670.02 1670.02 1715.02 1760.02 1760.12 1857.92
    71.2   72.35   73.41   73.46   73.64   72.56   71.38
                   70.21   70.26   70.44
Pier Skew, UpSta & Num, DnSta & Num=  ,1680.02, 2 ,1700.02, 2 , 0 , 0 , 0 ,,
    1.35    1.35
    49.6    70.3
    1.35    1.35
    49.6    70.3
Pier Skew, UpSta & Num, DnSta & Num=  ,1710.02, 2 ,1730.02, 2 , 0 , 0 , 0 ,,
    1.35    1.35
    49.6    70.3
    1.35    1.35
    49.6    70.3
BR Coef=-1 , 1 , 1 ,1.25, 0 ,,,.8,-1,2,0,
WSPro=,,,, 1 ,,,, 0 ,,,, 0 ,,,,-1 ,-1 ,-1 , 0 , 0 , 0 , 0 , 0
BC Design=,, 0 ,, 0 ,,,,,,

Type RM Length L Ch R = 1 ,6680    ,78.35,78.6,77.74
BEGIN DESCRIPTION:
6679.632--d/s face Wilcrest bridge;  surveyed channel
END DESCRIPTION:
XS GIS Cut Line= 6
     3057247.128    13814188.152     3057644.341    13812452.871
     3057505.141    13811462.365     3057480.172    13810796.524
     3057351.166    13810093.229     3057476.011    13808690.802
#Sta/Elev= 30
       0   70.61  300.01   69.99  346.46   68.33  546.22   70.27 1227.82   68.96
 1654.15   71.01 1713.12   59.37 1714.46   57.72 1765.89   71.56 2367.78   69.06
 2609.98   70.65 2700.81   68.36 2804.78   71.06 2971.68   69.25  3085.5   70.91
  3286.9   68.92 3391.97   71.42 3543.58   70.01 3757.08   72.55 3848.58   70.51
  3906.2   73.31 4424.77   73.31 4469.95   75.19 4590.43   75.61 4916.25   75.44
 4951.85   73.97 5068.37   76.27 5222.92   73.74  5268.1   75.29 5570.99   75.39
#Mann= 3 , 0 , 0
       0     .08       0 1654.15     .04       0 1765.89     .15       0
#XS Ineff= 2 , 0
       0    1636            1815       0
Permanent Ineff=
       T       T
Bank Sta=1654.15,1765.89
XS Rating Curve= 0
Exp/Cntr=.5,.3

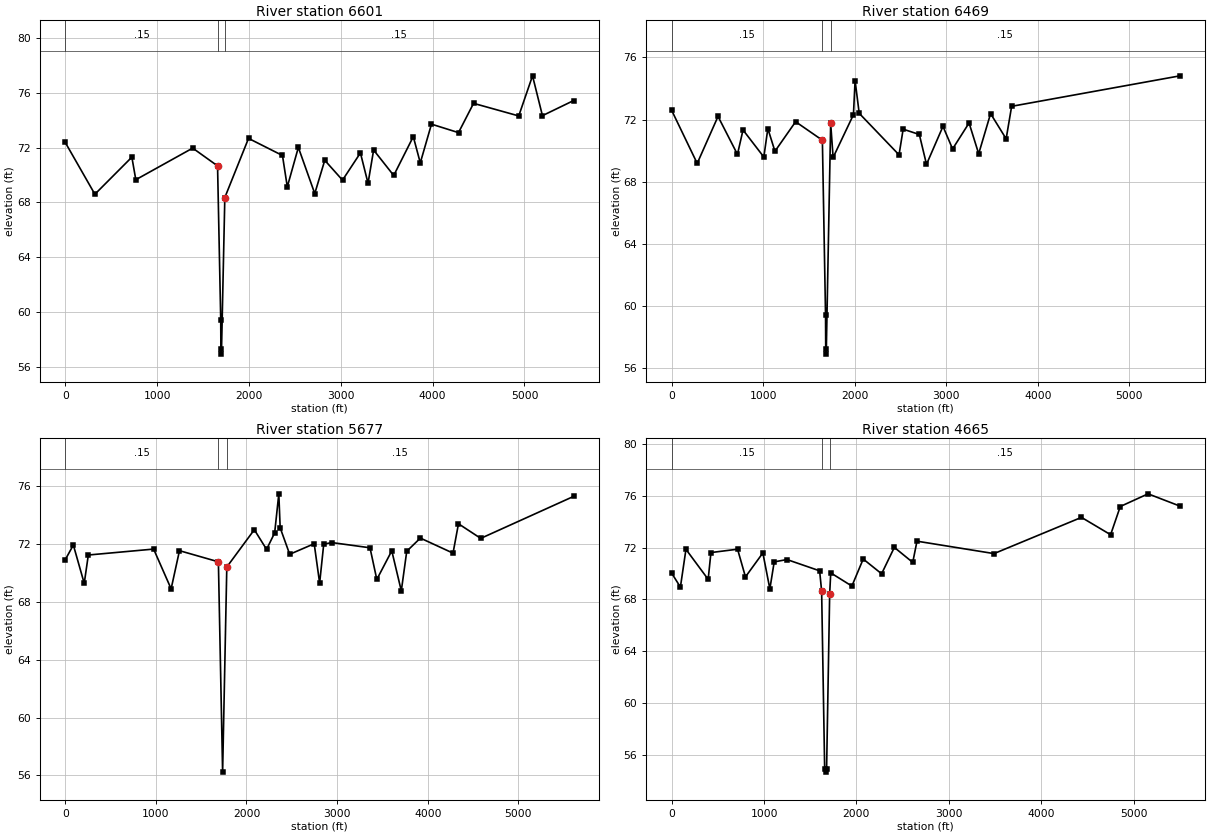
Type RM Length L Ch R = 1 ,6601    ,144.67,131.73,139.66
BEGIN DESCRIPTION:
6601.037--d/s exit Wilcrest bridge; channel copied from 6680
END DESCRIPTION:
XS GIS Cut Line= 6
     3057334.039    13814181.325     3057722.305     13812458.51
     3057621.664    13811479.011     3057613.341    13810833.977
     3057484.334    13810076.583     3057625.825    13808715.771
#Sta/Elev= 30
       0   72.39  323.03    68.6  725.55   71.31  768.61   69.66 1387.96   71.97
 1658.53   70.67 1693.14   59.41 1694.92   57.28 1700.66   56.92 1737.69   68.36
  1995.7   72.68 2365.22   71.43 2417.77   69.14 2538.15   72.02 2716.72   68.65
 2825.62   71.08 3018.85   69.63 3213.87   71.62 3296.73    69.4 3357.52   71.83
 3576.42   69.97 3789.43   72.81 3865.53   70.89 3987.26   73.72 4281.59    73.1
 4445.52   75.24  4937.3   74.32 5087.56   77.25 5195.31   74.34 5533.86   75.44
#Mann= 3 , 0 , 0
       0     .15       0 1658.53     .04       0 1737.69     .15       0
#XS Ineff= 2 , 0
       0    1630            1795       0
Permanent Ineff=
       T       T
Bank Sta=1658.53,1737.69
XS Rating Curve= 0
Exp/Cntr=.3,.1

Type RM Length L Ch R = 1 ,6469    ,798.06,792.39,786.69
BEGIN DESCRIPTION:
 6469.303--surveyed channel
END DESCRIPTION:
XS GIS Cut Line= 4
     3057603.411    13814203.315     3057845.714     13812587.04
     3057845.714    13812462.237     3057926.409     13808668.47
#Sta/Elev= 30
       0   72.59   278.9   69.18  506.41    72.2  718.76   69.76  779.43   71.33
 1006.94   69.59 1050.74   71.42 1128.28   69.96 1354.11   71.86 1646.54   70.67
 1681.15   59.41 1682.93   57.28 1688.67   56.92 1737.09   71.76 1763.88   69.56
 1985.89   72.31 2003.93    74.5 2048.94    72.4 2484.04   69.73 2529.05   71.38
 2705.75   71.04 2784.11   69.12 2964.15   71.56 3069.17   70.11 3249.21   71.78
 3354.24    69.8 3484.37   72.38 3654.31   70.76 3714.32   72.85 5553.77   74.81
#Mann= 3 , 0 , 0
       0     .15       0 1646.54     .04       0 1737.09     .15       0
#XS Ineff= 2 , 0
       0    1623            1784       0
Permanent Ineff=
       T       T
Bank Sta=1646.54,1737.09
XS Rating Curve= 0
Exp/Cntr=.3,.1

Type RM Length L Ch R = 1 ,5677    ,999.21,1011.98,1005.23
BEGIN DESCRIPTION:
 5676.917--surveyed channel
END DESCRIPTION:
XS GIS Cut Line= 4
     3058565.455    13814302.268     3058636.118    13812623.969
     3058637.944    13812498.044     3058451.793    13808699.375
#Sta/Elev= 30
       0   70.91   89.85   71.93  209.95   69.28  254.99   71.24  975.63   71.65
 1168.68    68.9 1260.88   71.54 1690.22   70.77 1736.87   56.23 1783.09   70.41
  2086.6   72.99 2221.77   71.63 2311.17   72.77 2356.93   75.47 2371.95   73.12
 2477.07   71.29  2747.4   72.02 2807.47    69.3 2852.52   71.99 2942.63    72.1
 3363.13   71.74 3438.22   69.55 3603.42   71.53 3708.55   68.76 3768.62    71.5
  3918.8   72.41 4279.23   71.37  4339.3    73.4  4585.2   72.39 5608.95   75.29
#Mann= 3 , 0 , 0
       0     .15       0 1690.22     .04       0 1783.09     .15       0
#XS Ineff= 2 , 0
       0    1646            1827       0
Permanent Ineff=
       T       T
Bank Sta=1690.22,1783.09
XS Rating Curve= 0
Exp/Cntr=.3,.1

Type RM Length L Ch R = 1 ,4665    ,64.01,62.25,61.28
BEGIN DESCRIPTION:
4664.936--u/s approach South Course bridge;  channel copied from 4551
END DESCRIPTION:
XS GIS Cut Line= 6
     3059412.092    13814231.861     3059452.749    13813519.712
       3059648.5    13812636.618       3059648.5     13812487.34
     3059384.822    13811220.089     3059252.974    13808782.355
#Sta/Elev= 30
       0   70.02   94.51   68.94  154.61   71.86     395   69.54  425.05   71.61
  713.31   71.87   798.8   69.73  987.01   71.58  1062.9    68.8 1109.92   70.89
  1248.2   71.07 1601.57    70.2  1623.3   68.64 1656.21   54.87 1665.49   54.64
 1676.98   54.85 1710.44   68.43 1721.96   70.04 1950.81   69.02 2073.38   71.11
 2272.55   69.97 2410.45   72.01 2609.62   70.85 2655.57   72.49 3489.72   71.53
  4436.1   74.33 4751.56   72.99 4856.33   75.17 5157.16   76.15 5502.81    75.2
#Mann= 3 , 0 , 0
       0     .15       0  1623.3     .04       0 1710.44     .15       0
#XS Ineff= 2 , 0
       0    1586            1765       0
Permanent Ineff=
       T       T
Bank Sta=1623.3,1710.44
XS Rating Curve= 0
Exp/Cntr=.5,.3