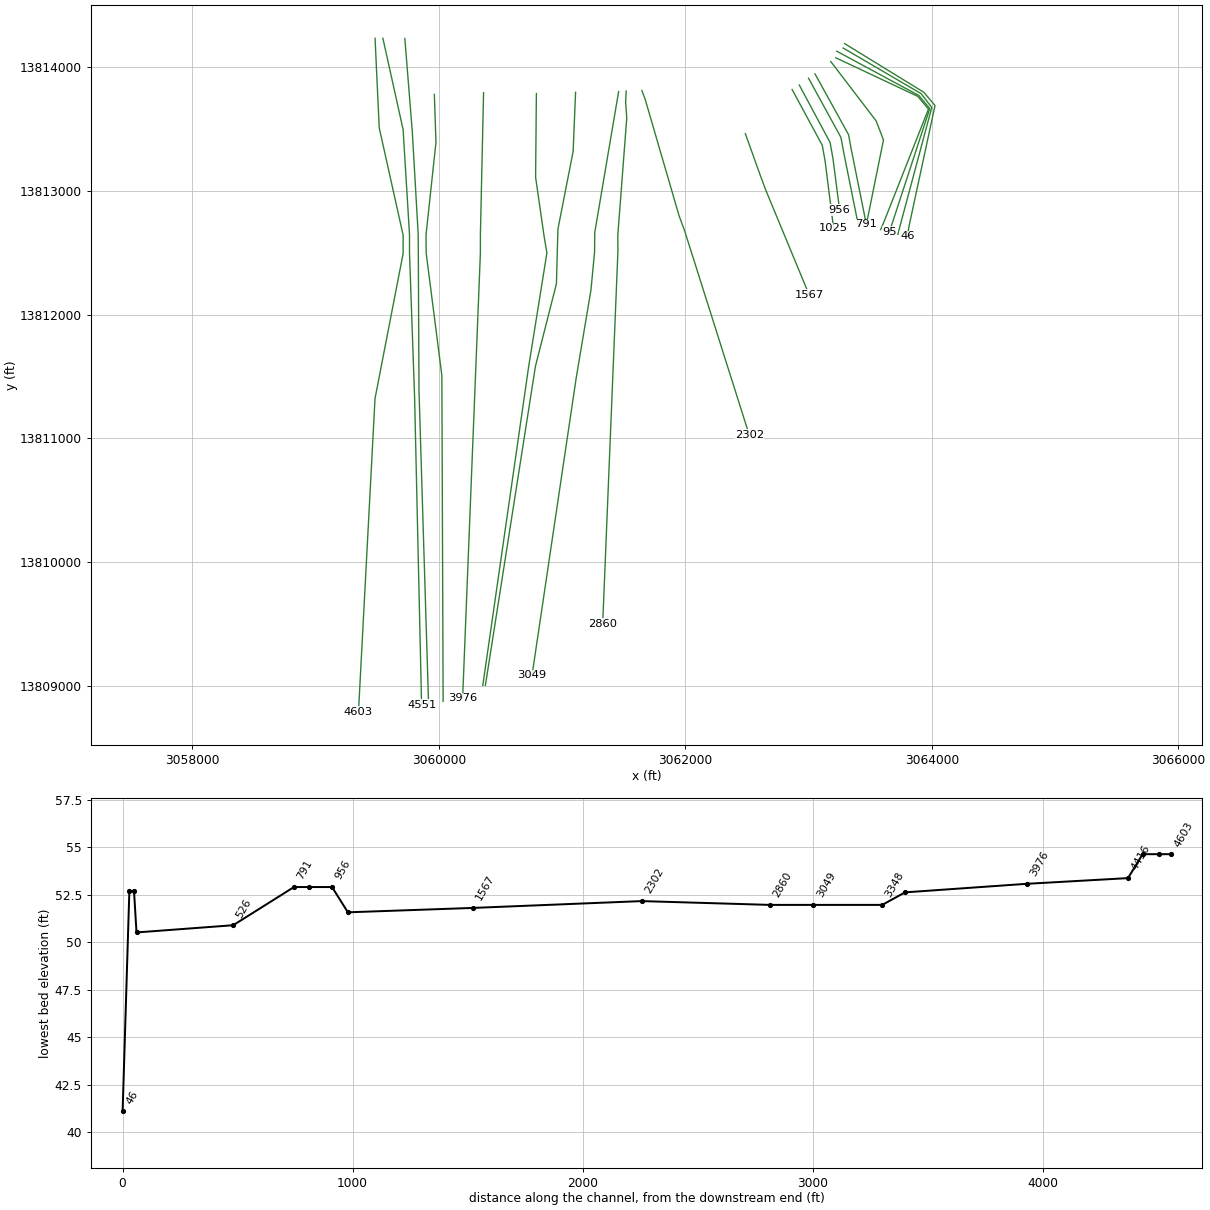
HEC-RAS study D120-00-00.prj: D120-00-00

--- D120-00-00.g01 (geometry) --- (continued)

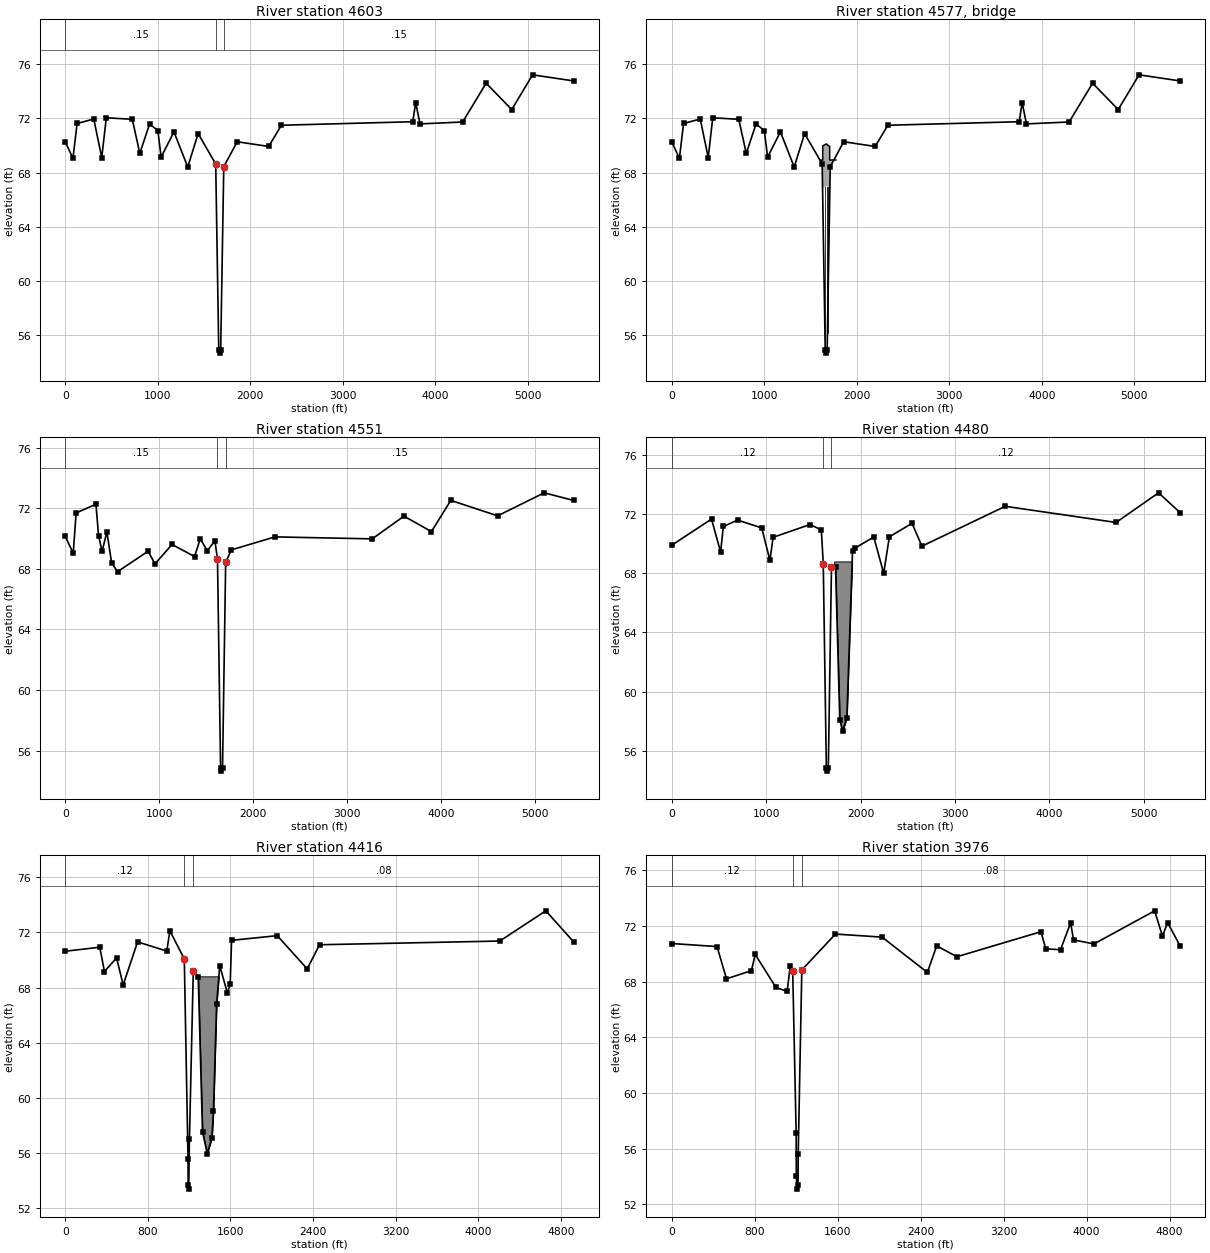
Type RM Length L Ch R = 1 ,4603    ,62.77,51.76,65.61
BEGIN DESCRIPTION:
4602.690--u/s face South Course bridge; channel copied form 4551
END DESCRIPTION:
XS GIS Cut Line= 6
     3059483.087    13814235.911     3059516.832    13813511.567
      3059710.74    13812644.233      3059710.74    13812494.955
     3059482.822    13811322.996     3059348.689    13808790.678
#Sta/Elev= 30
       0   70.28    83.5   69.05  128.55   71.63  308.75   71.96  394.88   69.11
  443.89   72.05  724.88   71.94  806.15   69.42  911.52   71.59 1001.27   71.11
  1036.7   69.14 1175.04   71.01 1324.02   68.41 1436.33   70.88  1626.3   68.64
 1659.21   54.87 1668.49   54.64 1679.98   54.85 1713.44   68.43  1858.7   70.28
 2198.62   69.93 2336.15    71.5  3755.6   71.76 3787.32   73.18 3833.79    71.6
 4294.88   71.74 4548.66   74.61 4825.18   72.66 5050.49   75.23 5492.94   74.78
#Mann= 3 , 0 , 0
       0     .15       0  1626.3     .04       0 1713.44     .15       0
#XS Ineff= 2 , 0
       0    1605            1779       0
Permanent Ineff=
       T       T
Bank Sta=1626.3,1713.44
XS Rating Curve= 0
Exp/Cntr=.5,.3

Type RM Length L Ch R = 3 ,4577    ,,,
BEGIN DESCRIPTION:
South Course Bridge
END DESCRIPTION:
Bridge Culvert--1,0,-1,-1, 0
Deck Dist Width WeirC Skew NumUp NumDn MinLoCord MaxHiCord MaxSubmerge Is_Ogee
11,30,2.6,0, 7, 7, , , .95, 0, 0,0,,
    1605 1632.37 1632.37 1669.87 1707.37 1707.47    1775
   68.92   68.92   69.97   70.12   69.93   68.93   68.93
     -.3     -.3   66.87   67.02   66.83     -.3     -.3
    1600 1627.37 1627.37 1664.87 1702.37 1702.47    1770
   68.92   68.92   69.97   70.12   69.93   68.93   68.93
     -.3     -.3   66.87   67.02   66.83     -.3     -.3
Pier Skew, UpSta & Num, DnSta & Num=  ,1657.57, 2 ,1652.57, 2 , 0 , 0 , 0 ,,
    1.35    1.35
    49.9    69.2
    1.35    1.35
    49.9    69.2
Pier Skew, UpSta & Num, DnSta & Num=  ,1683.17, 2 ,1678.17, 2 , 0 , 0 , 0 ,,
    1.35    1.35
    49.9    69.2
    1.35    1.35
    49.9    69.2
BR Coef=-1 , 1 , 1 ,1.25, 0 ,,,.8,-1,2,0,
WSPro=,,,, 1 ,,,, 0 ,,,, 0 ,,,,-1 ,-1 ,-1 , 0 , 0 , 0 , 0 , 0
BC Design=,, 0 ,, 0 ,,,,,,

Type RM Length L Ch R = 1 ,4551    ,70.87,71.09,69.57
BEGIN DESCRIPTION:
4550.926--d/s face South Course bridge; surveyed channel
END DESCRIPTION:
XS GIS Cut Line= 6
     3059546.614    13814235.911     3059710.709    13813496.729
     3059762.503    13812648.785     3059762.503    13812499.508
     3059804.054    13811325.609     3059860.554    13808844.777
#Sta/Elev= 30
       0   70.15   85.44   69.03  116.17   71.69  327.09   72.27  355.67   70.16
  392.74   69.16  443.69   70.44  493.98    68.4  556.85   67.81  881.64   69.16
  956.42   68.33 1137.11   69.61 1377.56   68.81 1437.67   69.99 1512.81   69.19
 1593.75   69.85  1621.3   68.64 1654.21   54.87 1663.49   54.64 1674.98   54.85
 1708.44   68.43 1767.99   69.25 2233.29   70.11 3268.81   69.98 3606.94   71.48
 3898.97   70.46 4105.72   72.52 4604.16    71.5 5099.28   73.02 5412.09   72.52
#Mann= 3 , 0 , 0
       0     .15       0  1621.3     .04       0 1708.44     .15       0
#XS Ineff= 2 , 0
       0    1613            1804       0
Permanent Ineff=
       T       T
Bank Sta=1621.3,1708.44
XS Rating Curve= 0
Exp/Cntr=.5,.3

Type RM Length L Ch R = 1 ,4480    ,73.42,63.59,71.82
BEGIN DESCRIPTION:
4479.839--d/s exit South Course bridge; channel copied from 4551; blocked obstruction in detention pond
END DESCRIPTION:
XS GIS Cut Line= 6
     3059724.727    13814233.998     3059785.346    13813477.852
       3059833.1     13812648.67     3059834.029    13812500.087
     3059839.585    13811384.892     3059917.179    13808855.525
#Sta/Elev= 30
       0   69.88   421.9   71.65  518.16   69.42  547.29   71.15  698.73   71.58
  954.25   71.05 1040.34   68.86 1074.45   70.42 1465.09   71.28 1585.29   70.92
  1605.3   68.64 1638.21   54.87 1647.49   54.64 1658.98   54.85 1692.44   68.43
  1735.3    68.4  1780.3   58.12  1810.3   57.33  1855.3   58.24  1915.3   69.47
 1937.78   69.67 2140.31   70.44 2245.31   67.99 2305.31   70.45 2545.31   71.36
 2650.31   69.82 3532.71   72.51 4706.19   71.42  5156.4   73.42 5383.48   72.09
#Mann= 3 , 0 , 0
       0     .12       0  1605.3     .04       0 1692.44     .12       0
#XS Ineff= 2 , 0
       0    1580            1825       0
Permanent Ineff=
       T       T
#Block Obstruct= 1 ,-1
 1721.37 1920.48   68.79
Bank Sta=1605.3,1692.44
XS Rating Curve= 0
Exp/Cntr=.3,.1

Type RM Length L Ch R = 1 ,4416    ,435.76,440.36,428.54
BEGIN DESCRIPTION:
4416.245--blocked obstruction in detention pond
END DESCRIPTION:
XS GIS Cut Line= 6
     3059964.075    13813782.149     3059977.201    13813394.445
     3059896.699    13812647.573     3059897.628     13812498.99
     3060024.943    13811509.293     3060035.337    13808873.908
#Sta/Elev= 30
       0   70.63  334.84   70.92  379.87   69.16  497.55   70.15  560.87   68.18
  700.46   71.31   983.3   70.64 1013.47   72.11 1152.81   70.07 1188.99   55.57
 1190.07   53.67 1195.59   53.38 1202.64   56.98 1239.94   69.22 1287.71   68.77
 1329.13   57.55 1374.91   55.96 1420.28    57.1 1435.41   59.08 1465.65   66.78
  1495.9   69.59 1570.32   67.59 1597.12   68.24 1610.52   71.42 2052.72   71.76
 2342.35   69.35 2462.36    71.1 4207.35   71.37 4652.37   73.56 4920.97   71.32
#Mann= 3 , 0 , 0
       0     .12       0 1152.81     .04       0 1239.94     .08       0
#XS Ineff= 2 , 0
       0    1114            1413       0
Permanent Ineff=
       T       T
#Block Obstruct= 1 ,-1
 1278.34 1488.61   68.81
Bank Sta=1152.81,1239.94
XS Rating Curve= 0
Exp/Cntr=.3,.1

Type RM Length L Ch R = 1 ,3976    ,507.17,529.09,529.46
BEGIN DESCRIPTION:
 3975.882--surveyed channel
END DESCRIPTION:
XS GIS Cut Line= 4
     3060363.385    13813795.762     3060337.516    13812643.208
     3060337.516    13812497.605     3060193.475    13808898.877
#Sta/Elev= 30
       0   70.74   437.3   70.52   528.4    68.2  768.46   68.79  805.66   69.95
 1005.19   67.58 1112.62    67.3 1143.32   69.11 1166.62   68.77 1199.99   57.11
  1201.5   53.99 1210.26   53.08 1217.48   53.36 1219.84   55.64 1254.58   68.84
 1578.78   71.42 2028.31    71.2 2464.48   68.66 2554.56   70.57 2749.71   69.79
 3560.36   71.59  3605.4   70.36 3748.48   70.29 3845.59   72.23 3873.58      71
 4070.77   70.71 4655.48   73.09  4731.3   71.27 4780.58   72.25 4900.05   70.58
#Mann= 3 , 0 , 0
       0     .12       0 1166.62     .04       0 1254.58     .08       0
#XS Ineff= 2 , 0
       0    1116            1517       0
Permanent Ineff=
       T       T
Bank Sta=1166.62,1254.58
XS Rating Curve= 0
Exp/Cntr=.3,.1

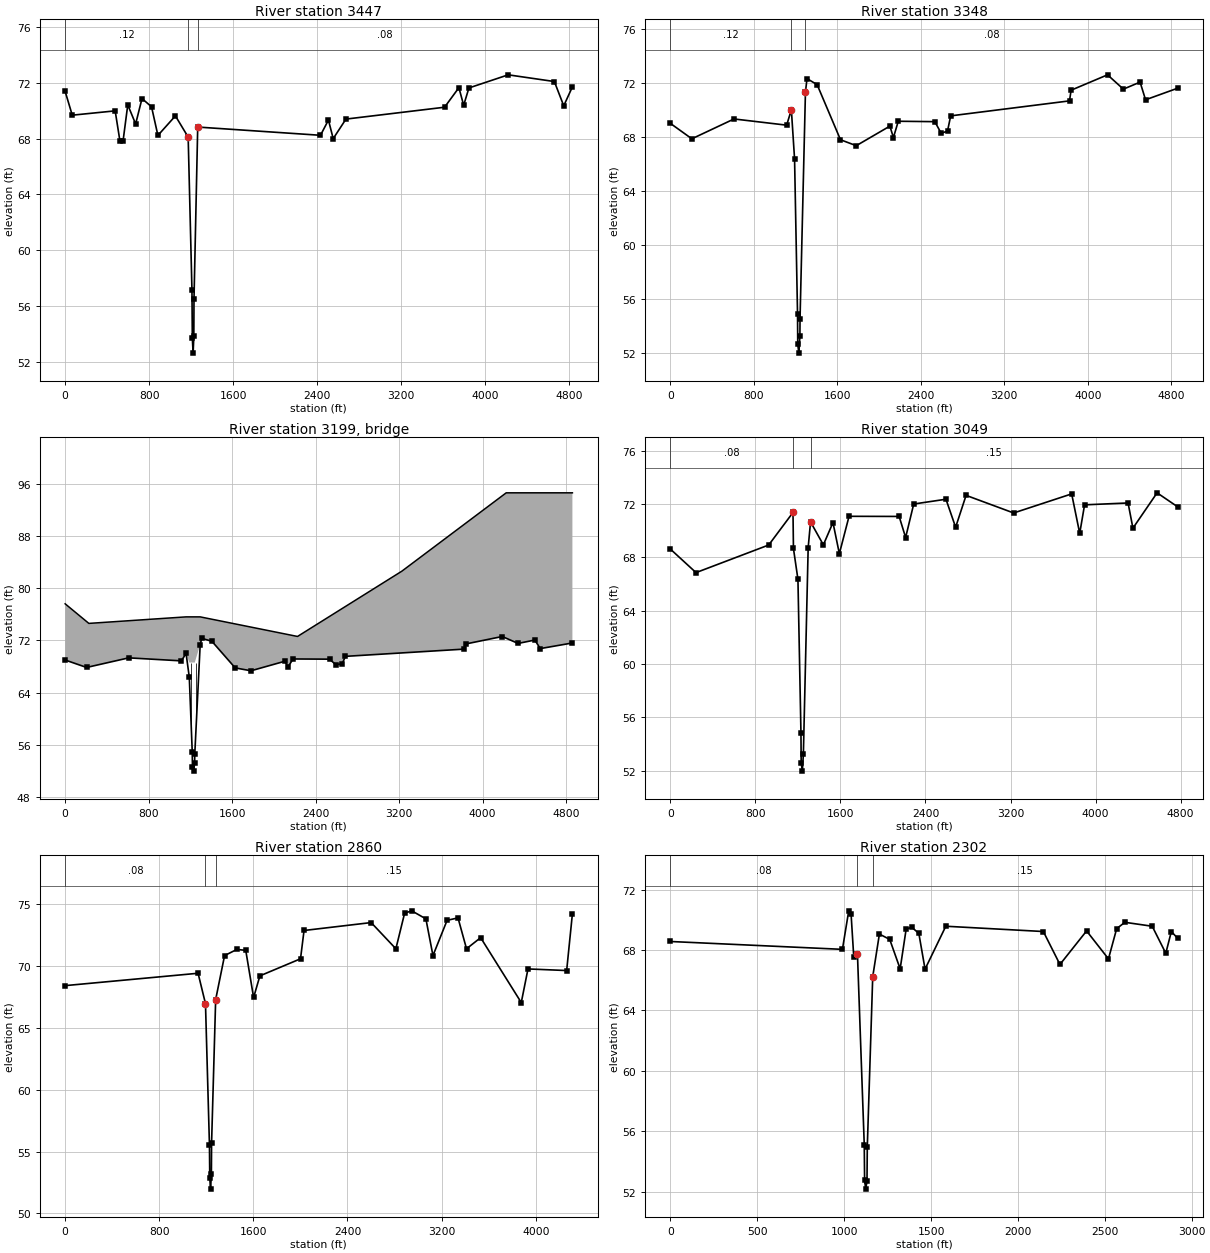
Type RM Length L Ch R = 1 ,3447    ,120.59,99.15,96.86
BEGIN DESCRIPTION:
3446.788--u/s appraoch Sam Houston Tollway bridge; surveyed channel
END DESCRIPTION:
XS GIS Cut Line= 6
     3060791.854    13813788.886     3060785.492    13813112.323
     3060854.044     13812637.08     3060877.122    13812499.592
     3060728.846    13811578.478     3060357.205    13809002.372
#Sta/Elev= 30
       0   71.37   67.67   69.67  476.41   69.98  521.41   67.84  551.41   67.81
  596.41   70.41  671.42   69.04  731.98   70.86  822.91   70.27  883.54   68.22
 1050.24   69.62 1171.81    68.1 1207.89   57.14 1211.39   53.72 1218.98   52.63
 1225.64   53.83 1227.28   56.49 1262.72   68.82  2432.2   68.23 2507.97   69.32
 2553.39   67.99 2674.68   69.39 3614.31   70.24 3750.71   71.64 3796.17   70.38
 3846.24   71.62 4220.52   72.56 4660.02   72.08 4749.46   70.34 4831.91    71.7
#Mann= 3 , 0 , 0
       0     .12       0 1171.81     .04       0 1262.72     .08       0
#XS Ineff= 2 , 0
       0    1134            1643       0
Permanent Ineff=
       T       T
Bank Sta=1171.81,1262.72
XS Rating Curve= 0
Exp/Cntr=.5,.3

Type RM Length L Ch R = 1 ,3348    ,303.2,298.81,293.98
BEGIN DESCRIPTION:
3347.633--u/s face Sam Houston Tollway bridge; channel copied from 3049
END DESCRIPTION:
XS GIS Cut Line= 6
     3061109.834    13813799.067     3061089.884    13813320.105
       3060966.5     13812691.89      3060954.57    13812250.907
     3060784.341    13811584.408     3060378.254     13809003.35
#Sta/Elev= 30
       0   68.99  205.34   67.85  609.48   69.32 1113.81   68.86 1159.04      70
 1189.78   66.35 1218.16   54.86  1220.2   52.61 1231.09   51.97 1240.93   53.24
 1242.18   54.53 1294.06   71.32 1309.07   72.31 1406.17   71.86 1629.83   67.78
 1781.11   67.34 2103.29   68.79 2137.18   67.94 2183.63   69.15 2534.12   69.12
 2594.86   68.26  2655.6   68.42 2685.97   69.55  3824.8   70.66 3839.99   71.45
 4189.23   72.59 4341.08   71.53 4501.28   72.05 4553.66   70.74 4861.55    71.6
#Mann= 3 , 0 , 0
       0     .12       0 1159.04     .04       0 1294.06     .08       0
#XS Ineff= 2 , 0
       0    1104            1671       0
Permanent Ineff=
       T       T
Bank Sta=1159.04,1294.06
XS Rating Curve= 0
Exp/Cntr=.5,.3

Type RM Length L Ch R = 3 ,3199    ,,,
BEGIN DESCRIPTION:
Sam Houston Tollway Bridge (modeled as one bridge)
END DESCRIPTION:
Bridge Culvert--1,0,-1,-1, 0
Deck Dist Width WeirC Skew NumUp NumDn MinLoCord MaxHiCord MaxSubmerge Is_Ogee
12,275,2.6,0, 8, 8, , , .95, 0, 0,0,,
       0  227.05 1159.05 1294.05 2227.05 3227.05 4227.05 4861.55
    77.6    74.6    75.6    75.6    72.6    82.6    94.6    94.6
     -.4     -.4    68.6    68.6     -.4     -.4     -.4     -.4
       0  236.43 1168.43 1303.43 2236.43 3236.43 4236.43 4772.94
    77.6    74.6    75.6    75.6    72.6    82.6    94.6    94.6
     -.4     -.4    68.6    68.6     -.4     -.4     -.4     -.4
Pier Skew, UpSta & Num, DnSta & Num=  ,1208.55, 2 ,1217.93, 2 , 0 , 0 , 0 ,,
     1.3     1.3
    49.6    69.6
     1.3     1.3
    49.6    69.6
Pier Skew, UpSta & Num, DnSta & Num=  ,1256.55, 2 ,1265.93, 2 , 0 , 0 , 0 ,,
     1.3     1.3
    49.9    69.9
     1.3     1.3
    49.9    68.9
BR Coef=-1 , 1 , 1 ,1.25, 0 ,,,.8,-1,2,0,
WSPro=,,,, 1 ,,,, 0 ,,,, 0 ,,,,-1 ,-1 ,-1 , 0 , 0 , 0 , 0 , 0
BC Design=,, 0 ,, 0 ,,,,,,

Type RM Length L Ch R = 1 ,3049    ,186.69,188.46,194.23
BEGIN DESCRIPTION:
3048.819--d/s face Sam Houston Tollway bridge; channel surveyed
END DESCRIPTION:
XS GIS Cut Line= 6
     3061458.994    13813804.411     3061265.136    13812663.474
     3061264.214    13812510.527     3061234.604    13812200.672
     3061114.716    13811488.048      3060756.81    13809085.944
#Sta/Elev= 30
       0   68.61   240.8   66.85  925.02   68.92 1153.38   71.36 1157.46   68.66
 1199.78   66.35 1228.16   54.86  1230.2   52.61 1241.09   51.97 1250.93   53.24
 1296.11   68.73 1318.47   70.65 1439.02   68.93 1529.43    70.6 1589.54   68.27
 1680.67   71.07  2152.2   71.06 2213.05   69.48  2289.1   71.99 2592.58   72.35
 2683.57   70.25 2781.92   72.64 3229.53   71.32 3775.49   72.75 3851.17   69.79
 3896.82   71.93 4306.29   72.07 4351.78   70.18 4579.27   72.83 4772.94   71.78
#Mann= 3 , 0 , 0
       0     .08       0 1153.38     .04       0 1318.47     .15       0
#XS Ineff= 2 , 0
       0     936            1663       0
Permanent Ineff=
       T       T
Bank Sta=1153.38,1318.47
XS Rating Curve= 0
Exp/Cntr=.5,.3

Type RM Length L Ch R = 1 ,2860    ,513.11,557.94,615.8
BEGIN DESCRIPTION:
2860.364--d/s exit Sam Houston Tollway bridge; channel surveyed
END DESCRIPTION:
XS GIS Cut Line= 6
     3061520.478    13813809.375      3061515.94    13813718.623
     3061525.016    13813591.569     3061452.441    13812644.061
      3061453.34    13812513.851     3061329.898    13809503.175
#Sta/Elev= 30
       0   68.43 1129.98   69.43  1192.9   66.97 1226.69   55.52 1229.35   52.87
 1235.88   51.97 1243.07   53.17 1244.71   55.69 1279.42    67.3 1355.14   70.86
 1460.23   71.36 1535.29   71.28 1601.93   67.47 1655.39   69.22 2000.68    70.6
 2030.71   72.89 2601.18   73.53 2811.36   71.41 2885.59   74.29 2946.48   74.48
 3066.58   73.83 3126.63   70.86 3246.73   73.71 3339.57   73.91 3411.87   71.41
 3531.97   72.31 3877.26   67.06 3934.44   69.78 4263.18   69.65 4311.95   74.24
#Mann= 3 , 0 , 0
       0     .08       0  1192.9     .04       0 1279.42     .15       0
#XS Ineff= 2 , 0
       0     855            1652       0
Permanent Ineff=
       T       T
Bank Sta=1192.9,1279.42
XS Rating Curve= 0
Exp/Cntr=.3,.1

Type RM Length L Ch R = 1 ,2302    ,758.25,735.33,745.44
BEGIN DESCRIPTION:
 2302.42--surveyed channel
END DESCRIPTION:
XS GIS Cut Line= 5
     3061647.531    13813813.913     3061674.757    13813741.311
     3061948.697    13812802.806     3061993.675     13812681.42
     3062518.754    13811027.815
#Sta/Elev= 30
       0   68.56  989.98   68.04 1026.27   70.59  1039.9   70.36 1055.21   67.53
  1076.4   67.76 1115.57   55.12 1117.59   52.79 1123.63   52.17 1131.39   52.68
  1133.1   54.96 1164.38   66.23 1202.77   69.05 1262.22    68.7 1322.22   66.75
 1356.64   69.37 1388.12   69.51 1429.73    69.1 1465.56   66.73 1585.01   69.57
 2146.43   69.22 2241.99   67.04 2395.36   69.26 2521.26   67.41 2568.48   69.41
 2615.69   69.83 2773.07   69.57 2851.19   67.78 2883.24   69.22 2919.63   68.77
#Mann= 3 , 0 , 0
       0     .08       0  1076.4     .04       0 1164.38     .15       0
#XS Ineff= 2 , 0
       0     650            1518       0
Permanent Ineff=
       T       T
Bank Sta=1076.4,1164.38
XS Rating Curve= 0
Exp/Cntr=.3,.1

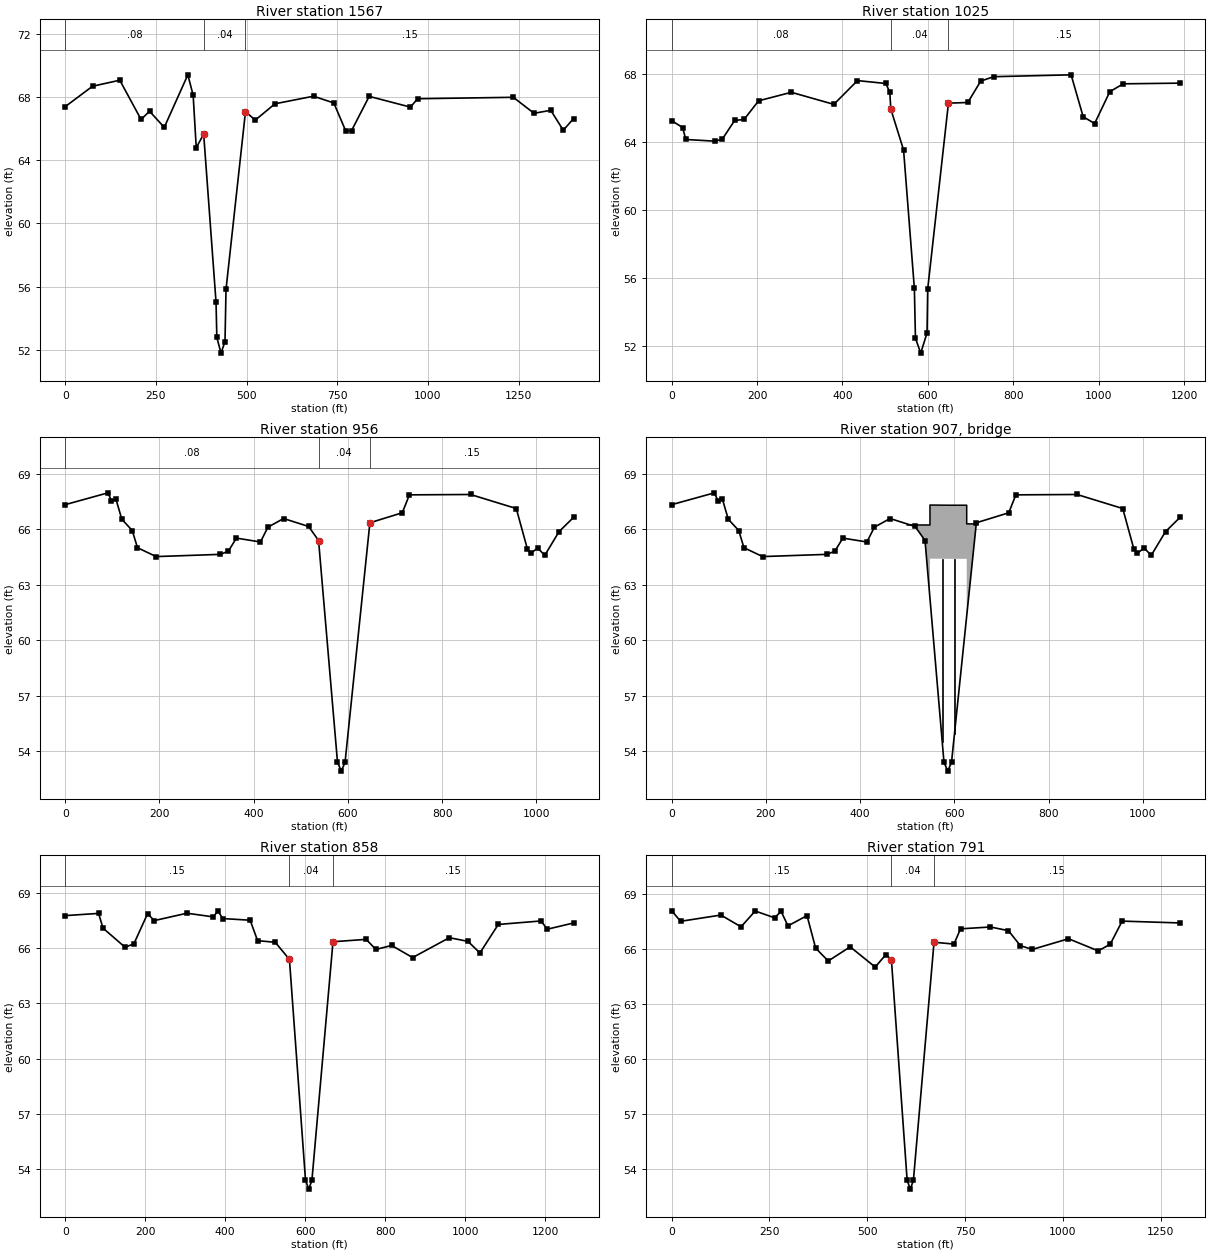
Type RM Length L Ch R = 1 ,1567    ,528.41,542.24,501.75
BEGIN DESCRIPTION:
 1567.093--surveyed channel
END DESCRIPTION:
XS GIS Cut Line= 4
     3062486.991    13813464.516     3062609.179    13813124.504
     3062654.222    13813004.441     3063004.279    13812162.219
#Sta/Elev= 30
       0   67.38   75.43   68.67   150.5   69.05  209.12   66.57  232.57   67.09
  273.11   66.07   338.1   69.39   352.8    68.1   361.3   64.79   381.8   65.64
  415.87   55.03   418.1    52.8  429.56   51.81  440.59   52.54  443.41   55.84
  497.05   67.06  524.13   66.53  578.27   67.56  684.77   68.04  740.71   67.61
   773.2   65.86  789.44   65.86  838.18   68.03  951.89   67.35  971.64   67.88
 1235.56   67.97 1292.75   66.96 1338.83   67.15 1373.26   65.89 1401.61   66.62
#Mann= 3 , 0 , 0
       0     .08       0   381.8     .04       0  497.05     .15       0
#XS Ineff= 2 , 0
       0     118             826       0
Permanent Ineff=
       T       T
Bank Sta=381.8,497.05
XS Rating Curve= 0
Exp/Cntr=.3,.1

Type RM Length L Ch R = 1 ,1025    ,67.24,68.91,70.59
BEGIN DESCRIPTION:
1024.854--u/s approach Club Creek bridge; surveyed channel
END DESCRIPTION:
XS GIS Cut Line= 5
     3062866.568    13813821.491     3063111.251    13813370.381
     3063134.497    13813240.796     3063199.653    13812725.052
     3063203.149    13812699.531
#Sta/Elev= 30
       0   65.28   25.76   64.87   32.98   64.17  101.24   64.07   118.3   64.18
  147.46   65.29  169.58   65.35  203.63   66.45  280.22   66.95  379.79   66.24
  435.11   67.64  501.49   67.47  510.78   66.96   513.2   65.96  543.08   63.55
  568.36   55.39  570.89   52.46  583.26   51.58  598.01   52.77  599.64   55.37
  648.17   66.31  693.53   66.35  723.77   67.61  754.01   67.87  935.44   67.98
   963.7   65.51  990.55   65.11 1026.15   66.99 1057.66   67.45 1190.45   67.49
#Mann= 3 , 0 , 0
       0     .08       0   513.2     .04       0  648.17     .15       0
#XS Ineff= 2 , 0
       0     520            1049       0
Permanent Ineff=
       T       T
Bank Sta=513.2,648.17
XS Rating Curve= 0
Exp/Cntr=.5,.3

Type RM Length L Ch R = 1 ,956     ,94.95,98.01,107.7
BEGIN DESCRIPTION:
955.940--u/s face Club Creek bridge; channel copied from 858
END DESCRIPTION:
XS GIS Cut Line= 5
     3062924.761    13813857.515     3063174.659    13813392.817
     3063197.905    13813263.233     3063248.695    13812872.555
     3063252.191    13812847.034
#Sta/Elev= 30
       0   67.33   90.85   67.97   98.02   67.54  107.88   67.61  120.17   66.54
  142.32   65.93   153.4      65  193.04   64.52  329.29   64.64  346.32   64.81
  363.35   65.52  414.45   65.31  430.28   66.11  463.51   66.58  516.64   66.15
  537.79   65.39  577.96    53.4  585.96   52.91  593.98   53.38  646.75   66.35
  715.48   66.89  730.61   67.86  860.37   67.88   957.5   67.12  980.84   64.95
  987.76   64.69 1002.88   64.98 1018.01   64.59 1048.26   65.87 1079.01   66.64
#Mann= 3 , 0 , 0
       0     .08       0  537.79     .04       0  646.75     .15       0
#XS Ineff= 2 , 0
       0     520            1060       0
Permanent Ineff=
       T       T
Bank Sta=537.79,646.75
XS Rating Curve= 0
Exp/Cntr=.5,.3

Type RM Length L Ch R = 3 ,907     ,,,
BEGIN DESCRIPTION:
Club Creek Bridge (width measured from aerial photo)
END DESCRIPTION:
Bridge Culvert--1,0,-1,-1, 0
Deck Dist Width WeirC Skew NumUp NumDn MinLoCord MaxHiCord MaxSubmerge Is_Ogee
19,60,2.6,0, 7, 7, , , .95, 0, 0,0,,
     500  548.27  548.27  587.27  626.27  626.27     650
   66.23   66.23   67.31    67.3    67.3   66.29   66.29
             -.3   64.41    64.4    64.4     -.3     -.3
     523  571.27  571.27  610.27  649.27  649.27     673
   66.23   66.23   67.31    67.3    67.3   66.29   66.29
             -.3   64.41    64.4    64.4     -.3     -.3
Pier Skew, UpSta & Num, DnSta & Num=  ,574.27, 2 ,597.27, 2 , 0 , 0 , 0 ,,
     1.5     1.5
    49.9    66.9
     1.5     1.5
    49.9    66.9
Pier Skew, UpSta & Num, DnSta & Num=  ,600.27, 2 ,623.27, 2 , 0 , 0 , 0 ,,
     1.5     1.5
    49.9    66.9
     1.5     1.5
    49.9    66.9
BR Coef=-1 , 1 , 1 ,1.25, 0 ,,,.8,-1,2,0,
WSPro=,,,, 1 ,,,, 0 ,,,, 0 ,,,,-1 ,-1 ,-1 , 0 , 0 , 0 , 0 , 0
BC Design=,, 0 ,, 0 ,,,,,,

Type RM Length L Ch R = 1 ,858     ,64.04,67.32,67.75
BEGIN DESCRIPTION:
857.931--d/s face Club Creek bridge; surveyed channel
END DESCRIPTION:
XS GIS Cut Line= 5
     3062999.581    13813912.937     3063262.753    13813433.684
     3063284.999    13813312.719     3063402.279    13812731.511
     3063404.336    13812723.093
#Sta/Elev= 30
       0   67.77   83.48   67.89   94.53   67.09  149.76   66.05  171.85   66.24
  205.85   67.87  222.97    67.5  304.41    67.9  370.69    67.7  381.74   68.03
  394.09   67.61  462.54   67.52  481.16   66.41  525.35   66.32  560.79   65.39
  600.96    53.4  608.96   52.91  616.98   53.38  669.75   66.35   752.7   66.48
  777.09   65.93  816.37   66.15   868.9   65.49  960.72   66.57 1007.36   66.37
 1037.23   65.74 1083.14   67.29 1190.25   67.48 1205.56   67.03 1271.34   67.37
#Mann= 3 , 0 , 0
       0     .15       0  560.79     .04       0  669.75     .15       0
#XS Ineff= 2 , 0
       0     518             944       0
Permanent Ineff=
       T       T
Bank Sta=560.79,669.75
XS Rating Curve= 0
Exp/Cntr=.5,.3

Type RM Length L Ch R = 1 ,791     ,213.51,264.35,263.4
BEGIN DESCRIPTION:
790.608--d/s exit Club Creek bridge;  channel copied from 858
END DESCRIPTION:
XS GIS Cut Line= 5
     3063052.232    13813947.576     3063324.559    13813455.979
     3063346.804    13813335.014     3063464.084    13812753.806
     3063467.045    13812732.331
#Sta/Elev= 30
       0   68.06   22.95   67.49  125.84   67.83  177.28   67.19  213.59   68.05
  263.02   67.68   279.8   68.03  297.32   67.24  346.01    67.8  368.08   66.03
   400.2   65.33  456.36    66.1  520.24      65  547.76   65.68  561.79   65.39
  601.96    53.4  609.96   52.91  617.98   53.38  670.75   66.35  721.66   66.25
  738.55   67.08  815.06   67.18  860.97   66.98  891.58   66.16  922.18   65.96
 1014.52   66.54 1090.51   65.88 1121.11   66.24 1151.72    67.5 1299.58    67.4
#Mann= 3 , 0 , 0
       0     .15       0  561.79     .04       0  670.75     .15       0
#XS Ineff= 2 , 0
       0     520             813       0
Permanent Ineff=
       T       T
Bank Sta=561.79,670.75
XS Rating Curve= 0
Exp/Cntr=.3,.1

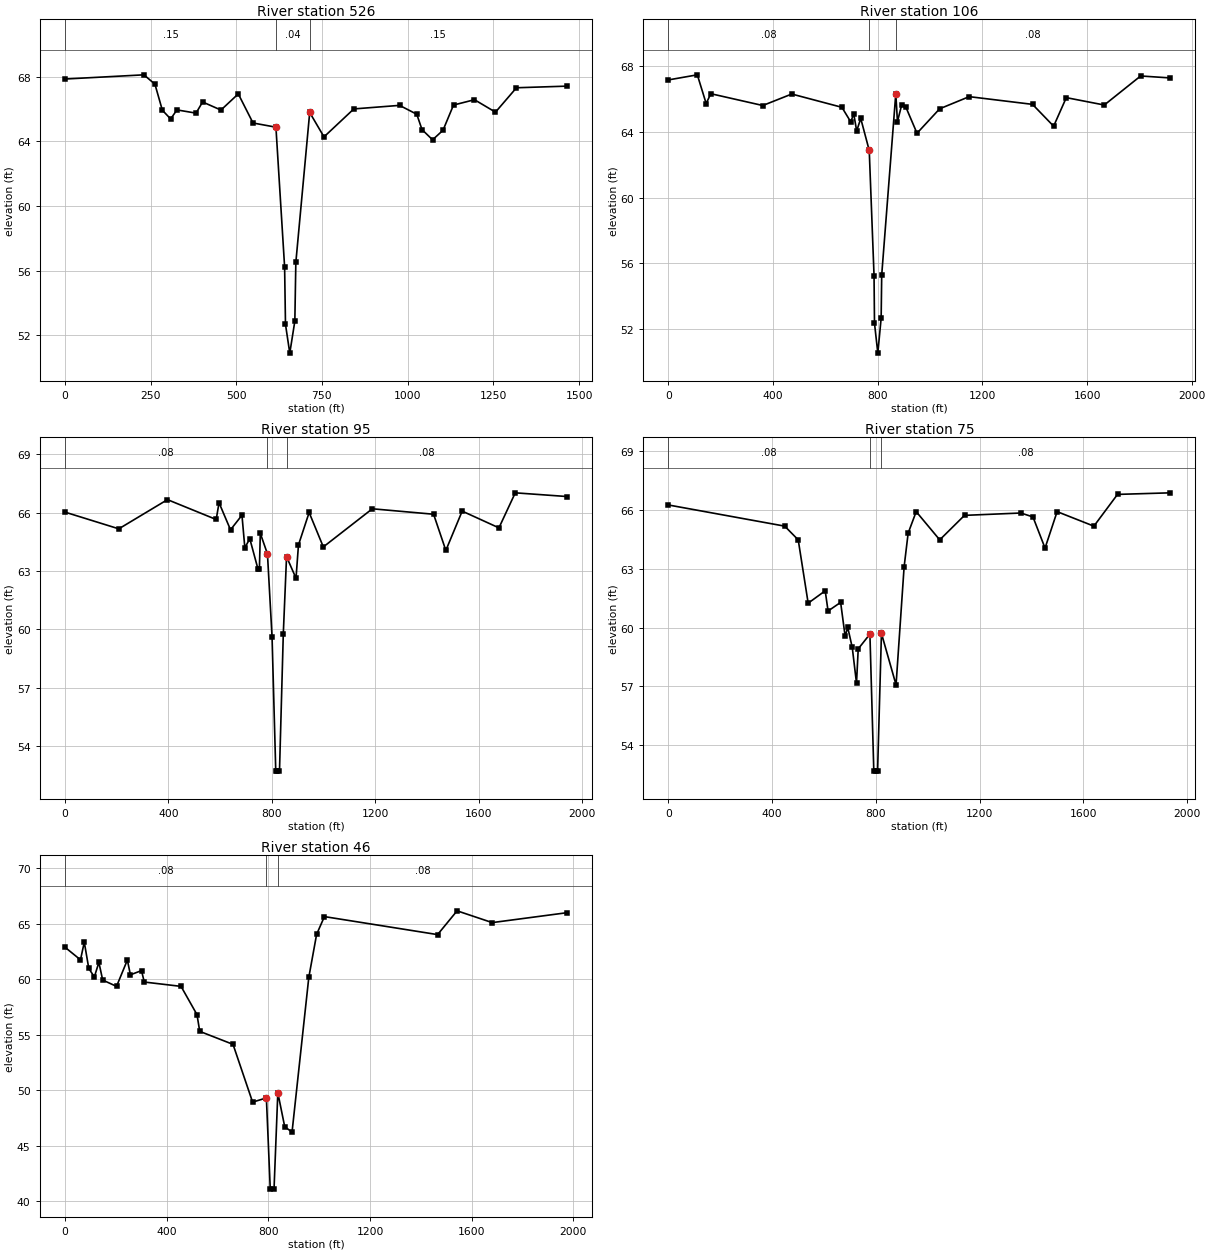
Type RM Length L Ch R = 1 ,526     ,232.93,420.33,332.04
BEGIN DESCRIPTION:
 526.258--surveyed channel
END DESCRIPTION:
XS GIS Cut Line= 6
     3063179.883    13814048.209     3063547.565      13813568.2
      3063587.67    13813466.239     3063607.484    13813412.683
     3063476.883    13812769.633     3063474.014    13812732.741
#Sta/Elev= 30
       0   67.86  230.62   68.12  262.72   67.54  284.32   65.93  308.53   65.39
  326.92   65.95  382.53   65.75  401.81   66.44  455.31   65.94  505.87   66.94
  548.85   65.14  615.68   64.88  641.02   56.23  643.57   52.68   656.1    50.9
  670.86   52.88  673.76   56.51  714.21   65.79  755.91   64.28  842.93   66.01
  976.45   66.23 1026.61   65.68 1041.91   64.73  1072.7    64.1 1103.14   64.69
 1133.75   66.25 1194.98   66.58  1256.2   65.81 1317.43   67.32  1464.5   67.42
#Mann= 3 , 0 , 0
       0     .15       0  615.68     .04       0  714.21     .15       0
#XS Ineff= 2 , 0
       0     552             768       0
Permanent Ineff=
       T       T
Bank Sta=615.68,714.21
XS Rating Curve= 0
Exp/Cntr=.3,.1

Type RM Length L Ch R = 1 ,106     ,30.12,10.93,24.85
BEGIN DESCRIPTION:
 105.928--surveyed channel
END DESCRIPTION:
XS GIS Cut Line= 6
     3063220.881    13814077.818     3063223.741    13814076.619
     3063886.406    13813765.739     3063972.817    13813663.358
     3063612.169    13812752.536     3063584.458    13812688.454
#Sta/Elev= 30
       0   67.17  110.52   67.48  144.36   65.73  161.89   66.33  360.72   65.61
  471.41   66.31  663.14    65.5  696.97   64.61  708.25   65.11  719.53   64.06
  735.07   64.82  767.57   62.87   785.9   55.25  787.62   52.34  800.37   50.52
  813.06   52.65   815.2   55.28  869.04   66.33  875.34   64.63  891.47   65.64
   907.6   65.51  950.13   63.92 1036.67   65.41  1149.6   66.15  1391.6   65.68
 1472.26   64.35 1520.66   66.09 1665.86   65.64  1804.8   67.41 1918.48   67.29
#Mann= 3 , 0 , 0
       0     .08       0  767.57     .04       0  869.04     .08       0
#XS Ineff= 2 , 0
       0     643             988       0
Permanent Ineff=
       T       T
Bank Sta=767.57,869.04
XS Rating Curve= 0
Exp/Cntr=.3,.1

Type RM Length L Ch R = 1 ,95      ,34.73,20.18,28.02
BEGIN DESCRIPTION:
 94.998--surveyed channel
END DESCRIPTION:
XS GIS Cut Line= 6
     3063228.852    13814130.773     3063231.862    13814129.409
     3063894.301    13813773.268     3063983.315    13813667.802
     3063671.055    13812716.165     3063657.199    13812672.867
#Sta/Elev= 30
       0   66.03  208.39   65.17  396.53   66.67  584.82   65.65  595.89   66.51
   640.2   65.12   684.5   65.87  695.58    64.2   714.8   64.66  746.47    63.1
  751.86    63.1  755.41   64.94  783.04   63.88   800.8   59.62  815.07   52.75
  821.41   52.72  829.57   52.73  844.25   59.77  856.83   63.74  893.42   62.63
   902.9   64.34  944.15   66.01  998.98   64.24 1188.42    66.2 1425.23   65.92
 1472.59   64.06 1535.74   66.08 1677.82   65.22 1740.97   67.02 1940.44   66.83
#Mann= 3 , 0 , 0
       0     .08       0  783.04     .04       0  856.83     .08       0
#XS Ineff= 2 , 0
       0     659            1012       0
Permanent Ineff=
       T       T
Bank Sta=783.04,856.83
XS Rating Curve= 0
Exp/Cntr=.3,.1

Type RM Length L Ch R = 1 ,75      ,28.72,29.26,36.27
BEGIN DESCRIPTION:
 74.821--surveyed channel
END DESCRIPTION:
XS GIS Cut Line= 6
     3063279.814    13814156.966     3063282.622    13814155.804
     3063912.405    13813788.284     3063999.587    13813676.512
     3063742.065    13812717.897     3063724.745    13812650.352
#Sta/Elev= 30
       0   66.26  448.66   65.18  500.76   64.48   539.1   61.25  604.81   61.88
  615.87   60.85  664.33   61.29  681.68   59.56   691.8   60.01  709.17   58.99
  725.55   57.17  732.21   58.92  777.29   59.67   792.3   52.69  799.52   52.68
  806.87   52.68  821.75   59.71  878.12   57.08  909.19    63.1  924.72   64.82
  955.78   65.92 1046.59   64.48 1142.16   65.73 1359.61   65.85  1406.2   65.65
  1452.8   64.06 1499.39   65.92 1641.22   65.18 1732.37    66.8  1936.3   66.88
#Mann= 3 , 0 , 0
       0     .08       0  777.29     .04       0  821.75     .08       0
#XS Ineff= 2 , 0
       0     626             997       0
Permanent Ineff=
       T       T
Bank Sta=777.29,821.75
XS Rating Curve= 0
Exp/Cntr=.3,.1

Type RM Length L Ch R = 1 ,46      ,15.37,45.56,25.53
BEGIN DESCRIPTION:
 45.56--surveyed channel
END DESCRIPTION:
XS GIS Cut Line= 6
     3063293.318    13814192.819     3063302.926     13814186.26
      3063935.85    13813798.429      3064025.85    13813691.944
      3063818.27    13812731.753     3063800.951    13812634.764
#Sta/Elev= 30
       0   62.88   61.33   61.74   76.25   63.33   94.05   60.96  115.87    60.2
  133.67   61.51  148.59   59.92  203.13   59.35  245.69   61.72  257.67   60.39
   301.3   60.77  312.21   59.74   456.8   59.35  519.46   56.81  530.37    55.3
  661.27   54.13  738.27   48.93  792.44   49.31  807.72    41.1  822.61   41.15
  837.42   49.78  864.54   46.72  893.36   46.23  959.29   60.16  989.98   64.03
 1020.67   65.63 1465.72   64.01 1542.46   66.15 1680.57   65.09 1974.25   65.98
#Mann= 3 , 0 , 0
       0     .08       0  792.44     .04       0  837.42     .08       0
#XS Ineff= 2 , 0
       0     630            1028       0
Permanent Ineff=
       T       T
Bank Sta=792.44,837.42
XS Rating Curve= 0
Exp/Cntr=.3,.1

Chan Stop Cuts=-1